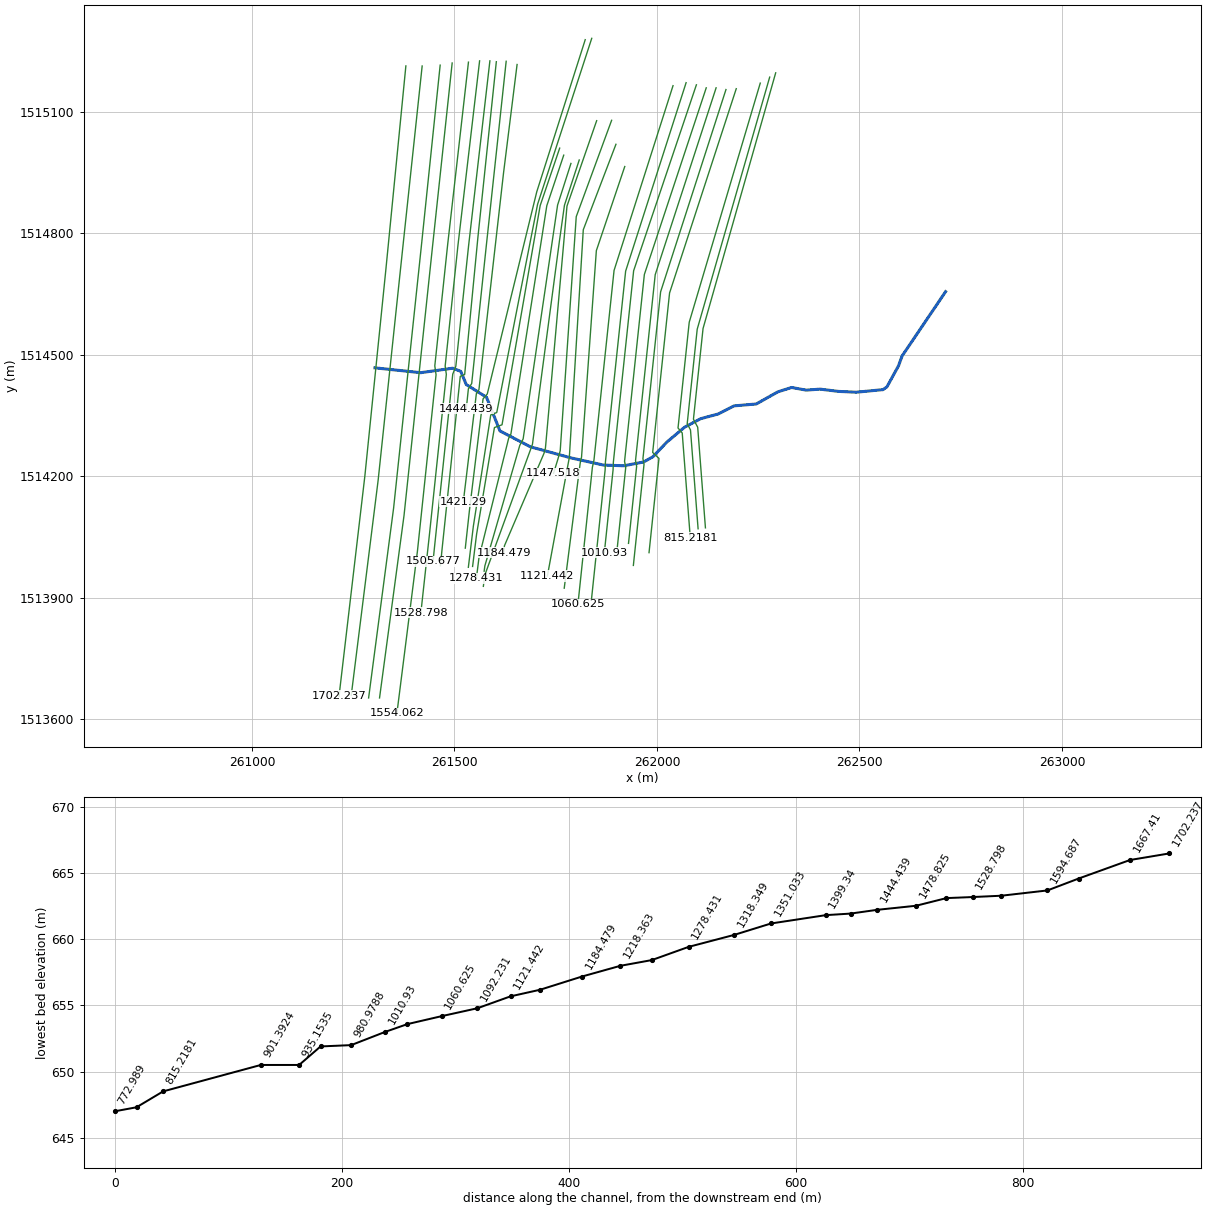
--- amss1_V6.prj (project) ---

Proj Title=amss1_V6
Current Plan=p01
Default Exp/Contr=0.3,0.1
SI Units
Geom File=g01
Flow File=f01
Plan File=p01
Y Axis Title=Elevation
X Axis Title(PF)=Main Channel Distance
X Axis Title(XS)=Station
BEGIN DESCRIPTION:
END DESCRIPTION:
DSS File=dss
DSS Export Rating Curves= 0
DSS Export Rating Curve Sorted= 0
DSS Export Volume Flow Curves= 0
DXF OffsetX= 0
DXF OffsetY= 0
DXF ScaleX= 1
DXF ScaleY= 10

--- amss1_V6.p01 (plan) ---

Plan Title=Plan 01
Program Version=4.10
Short Identifier=Plan 01
Geom File=g01
Flow File=f01
Subcritical Flow
K Sum by GR= 0
Std Step Tol= 0.003
Critical Tol= 0.003
Num of Std Step Trials= 20
Max Error Tol= 0.1
Flow Tol Ratio= 0.001
Split Flow NTrial= 30
Split Flow Tol= 0.006
Split Flow Ratio= 0.02
Log Output Level= 0
Friction Slope Method= 1
Unsteady Friction Slope Method= 2
Unsteady Bridges Friction Slope Method= 1
Parabolic Critical Depth
Global Vel Dist= 0 , 0 , 0
Global Log Level= 0
CheckData=True
Encroach Param=-1 ,0,0, 0
Computation Interval=1HOUR
Output Interval=1HOUR
Run HTab= 0
Run UNet= 0
Run PostProcess= 0
Run WQNet= 0
UNET Theta= 1
UNET Theta Warmup= 1
UNET ZTol= 0.006
UNET ZSATol= 0.015
UNET MxIter= 20
UNET MaxInSteps= 0
UNET DtIC= 0
UNET DtMin= 0
UNET MaxCRTS= 20
UNET WFStab= 2
UNET SFStab= 1
UNET WFX= 1
UNET SFX= 1
UNET DSS MLevel= 4
UNET DZMax Abort= 30
UNET Convert EG Bridges= 0
UNET Use Existing IB Tables=-1
UNET Froude Reduction=False
UNET Froude Limit= 1
UNET Froude Power= 10
UNET Time Slicing=0,0, 5
UNET Junction Losses=0
Instantaneous Interval=1HOUR
DSS File=dss
Write IC File= 0
Write IC File at Sim End=0
Echo Input=False
Echo Parameters=False
Echo Output=False
Write Detailed= 0
WQ AD Non Conservative
WQ ULTIMATE=-1
WQ Max Comp Step=1HOUR
WQ Output Interval=15MIN
WQ Output Selected Increments= 0
WQ Output face flow=0
WQ Output face velocity=0
WQ Output face area=0
WQ Output face dispersion=0
WQ Output cell volume=0
WQ Output cell surface area=0
WQ Output cell continuity=0
WQ Output cumulative cell continuity=0
WQ Output face conc=0
WQ Output face dconc_dx=0
WQ Output face courant=0
WQ Output face peclet=0
WQ Output face adv mass=0
WQ Output face disp mass=0
WQ Output cell mass=0
WQ Output cell source sink temp=0
WQ Output cell source sink nsm=0
WQ Output MaxMinRange=-1
WQ Daily Max Min Mean=-1
WQ Daily Range=0
WQ Daily Time=0
WQ Create Restart=0
WQ Fixed Restart=0
WQ System Summary=0
WQ Use Fixed Temperature=0
Sorting and Armoring Iterations= 10
XS Update Threshold= 0.02
Hydraulics Update Threshold= 0.02
Energy Slope Method= 1
Volume Change Method= 0
XS Weighting Method= 0
Number of US Weighted Cross Sections= 1
Number of DS Weighted Cross Sections= 1
Upstream XS Weight=0.25
Main XS Weight=0.5
Downstream XS Weight=0.25
Number of DS XS's Weighted with US Boundary= 1
Upstream Boundary Weight= 1
Weight of XSs Associated with US Boundary= 0
Number of US XS's Weighted with DS Boundary= 1
Downstream Boundary Weight= 0.5
Weight of XSs Associated with DS Boundary= 0.5
Sediment Output Level= 4
Mass or Volume Output= 0
Output Increment Type= 1
Profile and TS Output Increment= 10
XS Output Flag= 0
XS Output Increment= 10
Disregard all LS=0
Disregard all Conn=0
Disregard all Breaches=0
Disregard all Pumps=0

--- amss1_V6.f01 (steady flow) ---

Flow Title=Steady_DT12E
Program Version=5.03
Number of Profiles= 5
Profile Names=Escenario 1,Escenario 2,Escenario 3,Escenario 4,Escenario 5
River Rch & RM=Acelhuate,amss1           ,1702.237
    4.31    8.93   13.55   18.17   22.79
Boundary for River Rch & Prof#=Acelhuate,amss1           , 1
Up Type= 0
Dn Type= 3
Dn Slope=0.0105
DSS Import GetInterval= 0
DSS Import GetPeak= 0
DSS Import FillOption= 0

--- amss1_V6.g01 (geometry) ---

Geom Title=amss1_v6
Program Version=4.10

River Reach=Acelhuate       ,amss1
Reach XY= 30
261303.8500319021514467.38997957261416.9400319021514455.40997957
261495.7100319011514466.48997957261515.6600319021514458.73997957
261529.2000319021514426.18997957261579.3200319021514394.71997957
261612.4400319021514311.62997957261687.7400319021514272.37997957
261788.2300319021514244.92997957261867.8000319021514227.38997957
261918.1700319011514225.59997957261967.0100319021514234.91997957
261990.1000319021514247.84997957262024.3700319021514283.97997957
262068.5900319021514321.05997957262108.0200319021514341.86997957
262151.1200319021514353.41997957262190.3900319021514373.45997957
262245.2000319021514378.17997957262298.5600319021514408.09997957
262332.4700319021514418.86997957262368.3000319021514412.35997957
262402.7200319021514414.81997957262448.0500319021514409.23997957
262491.8100319021514407.19997957262558.1100319021514413.54997957
262567.8300319021514420.36997957262596.2600319021514472.03997957
262605.3200319021514496.69997957262712.6600319021514655.46997957

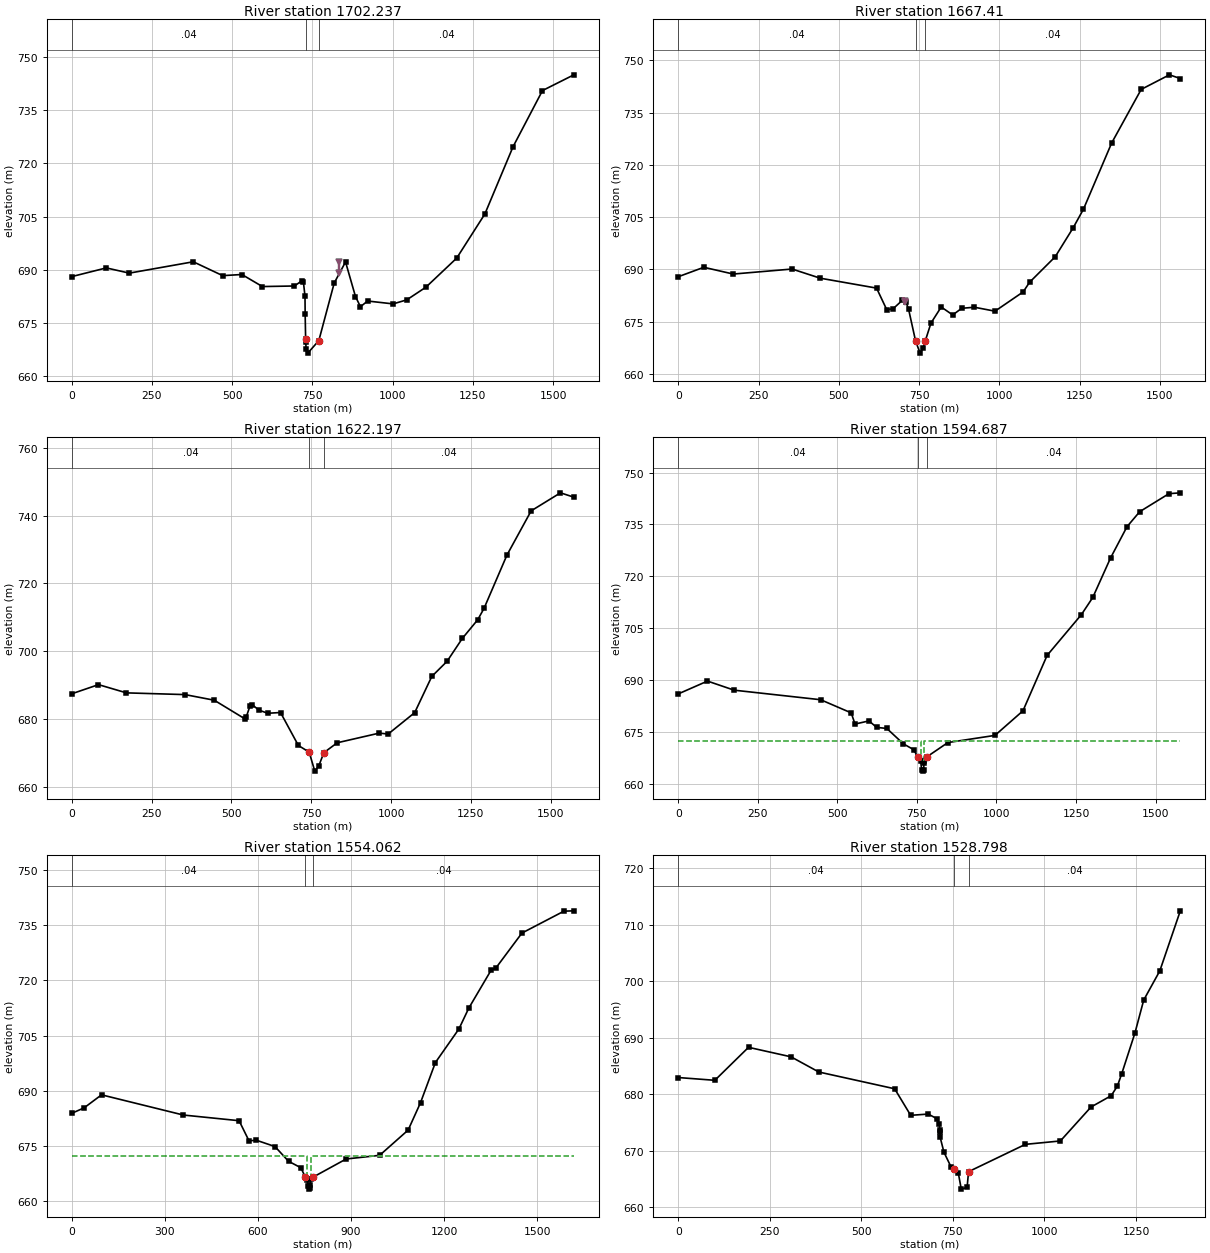
Type RM Length L Ch R = 1 ,1702.237,34.96,34.83,34.75
XS GIS Cut Line= 6
261380.1808319021515212.81737957261331.0700319021514713.06997957
261283.3500319021514243.89997957261279.5500319021514206.43997957
261278.8700319021514199.83997957261215.1863319021513657.08187957
#Sta/Elev= 30
       0  688.09   107.6  690.54  179.34  689.07  378.61  692.27  470.27  688.36
  530.13  688.68  594.05  685.28  693.94  685.44  717.91  686.97  721.91  686.49
 726.765  682.52 727.264  677.43 728.744  670.45 729.466  669.69   729.9 667.545
  735.37   666.5  769.85  670.03   817.8  686.28  853.09  692.23  884.09  682.46
  899.58  679.58  921.73   681.2 1001.43  680.39 1043.96  681.53  1103.8  685.12
 1199.53  693.31 1287.29  705.76 1375.04  724.72 1466.79  740.57 1564.52  745.01
#Mann= 3 , 0 , 0
       0     .04       0 728.744     .03       0  769.85     .04       0
Levee=0,,,-1,833.78,692.23,,Levee 1
Bank Sta=728.744,769.85
XS Rating Curve= 0 ,0
Exp/Cntr=0.3,0.1

Type RM Length L Ch R = 1 ,1667.41 ,45.25,45.21,45.22
XS GIS Cut Line= 6
261420.3877319021515212.59357957261370.9400319021514749.01997957
261369.4800319021514735.13997957261369.0500319021514731.17997957
261311.7200319021514190.01997957261245.3019319021513658.75757957
#Sta/Elev= 30
       0  687.91   79.69  690.62  171.34  688.68  354.63  690.12  442.29  687.49
   617.7  684.65   649.6  678.42  669.53  678.76  697.44  681.11   709.4  680.63
  717.37  678.61   739.3  669.45  753.25     666  763.22  667.49   769.2  669.45
  787.14  674.62  819.04  679.23  854.92  676.95  882.82  678.86  922.69  679.16
  986.48  678.03 1074.28  683.56 1094.26  686.32 1174.17  693.65  1230.1  701.96
 1262.07  707.29 1349.96  726.28 1441.86  741.64 1529.76  745.82 1563.72  744.76
#Mann= 3 , 0 , 0
       0     .04       0   739.3     .03       0   769.2     .04       0
Levee=-1,705.47,680.99,0,,,Levee 2,
Bank Sta=739.3,769.2
XS Rating Curve= 0 ,0
Exp/Cntr=0.3,0.1

Type RM Length L Ch R = 1 ,1622.197,27.54,27.51,27.51
XS GIS Cut Line= 6
261464.8378319021515214.71027957261418.0900319021514764.87997957
261414.9300319021514735.12997957261404.4300319021514635.92997957
261349.8900319021514121.16997957261288.1645319011513652.40757957
#Sta/Elev= 30
       0  687.43   83.68  690.13  171.34   687.7  354.63  687.19  446.28  685.53
  542.03  680.04  546.02  680.49  557.99  683.78  565.97  684.15  585.92  682.61
  613.85  681.68  653.76   681.9  709.62  672.18  743.53   670.2  761.02   664.6
  773.35  666.09  789.42  670.04  831.31  672.97  962.99  675.82  990.92  675.55
 1073.98  681.87  1127.5  692.55 1175.38  697.02 1223.26  703.79 1271.14  709.26
 1291.09  712.64 1362.91  728.38 1438.72  741.43 1530.49  746.75 1572.38  745.47
#Mann= 3 , 0 , 0
       0     .04       0  743.53     .03       0  789.42     .04       0
Bank Sta=743.53,789.42
XS Rating Curve= 0 ,0
Exp/Cntr=0.3,0.1

Type RM Length L Ch R = 1 ,1594.687,37.58,40.63,43.72
XS GIS Cut Line= 6
261494.4711319021515220.00187957261445.5500319021514763.00997957
261425.9700319021514578.09997957261425.7500319021514576.11997957
261375.6200319021514102.91997957261315.1521319021513652.40757957
#Sta/Elev= 30
       0  686.02   91.92  689.73  175.85   687.1  447.61  684.34  543.58  680.54
  555.58  677.31  599.56  678.22  623.55  676.34  655.54  676.04  707.53  671.59
  739.52  669.93  752.45  667.92  761.75  666.58   765.1  664.12  768.41   663.7
  771.16  663.98  772.26  665.94  773.82  666.55  780.34  667.76  847.48  671.96
  995.44  674.03 1083.41  681.13 1159.28  697.15 1266.94  708.93 1302.82   713.9
 1358.65  725.31 1410.48  734.37 1450.36   738.7 1542.07   743.9 1577.95  744.15
#Mann= 3 , 0 , 0
       0     .04       0  752.45    .038       0  780.34     .04       0
#XS Ineff= 2 , 0
       0  761.65  672.34  773.82       0  672.34
Permanent Ineff=
       F       F
Bank Sta=752.45,780.34
XS Rating Curve= 0 ,0
Exp/Cntr=0.3,0.1

Type RM Length L Ch R = 1 ,1554.062,26.11,25.26,26.15
XS GIS Cut Line= 6
261534.6879319021515222.11857957261483.3100319021514771.39997957
261451.6100319021514472.21997957261454.6900319021514450.34997957
261408.7900319021514015.42997957261358.0147319021513614.30747957
#Sta/Elev= 30
       0   683.9   39.97  685.39   95.92  688.92  359.71  683.43  539.31  681.89
  571.18  676.43  595.09  676.58  654.87  674.87   698.7  670.87  738.55   669.1
  752.79  666.54  758.79  665.73  760.08  664.04  764.72   663.3  768.15  663.49
  769.44  664.44  770.32  666.11  778.57   666.6   884.4  671.49  992.24  672.48
  1084.1  679.34 1124.04  686.78 1171.97  697.69 1247.77  706.81 1279.64  712.48
 1351.34  722.75 1367.28  723.41 1450.93  732.87 1586.38  738.82 1618.24  738.91
#Mann= 3 , 0 , 0
       0     .04       0  752.79    .038       0  778.57     .04       0
#XS Ineff= 2 , 0
       0     758  672.34     771       0  672.34
Permanent Ineff=
       F       F
Bank Sta=752.79,778.57
XS Rating Curve= 0 ,0
Exp/Cntr=0.3,0.1

Type RM Length L Ch R = 1 ,1528.798,26.88,23.12,16.34
XS GIS Cut Line= 6
261562.2046319021515225.29357957261508.8400319021514770.57997957
261477.1800319021514471.77997957261480.0700319021514451.26997957
261438.5000319021514057.39997957261417.2150552361513862.69851315
#Sta/Elev= 30
       0  682.96   99.96  682.47  191.93  688.31  307.89  686.63  383.86  683.94
  590.93  680.97  634.71  676.27  682.47  676.49  706.34  675.68  712.31   674.8
   714.5  673.73 715.034  673.25   715.2  672.38  725.49  669.74  744.96  667.12
  752.92  666.78  764.87  666.01  772.83   663.2  788.75   663.5  792.73  666.29
  947.97  671.13  1043.5  671.73 1127.09  677.74 1182.13  679.74 1199.06  681.44
 1211.05  683.65 1247.03  690.84 1271.01  696.68 1314.98  701.85 1370.94  712.48
#Mann= 3 , 0 , 0
       0     .04       0  752.92     .03       0  792.73     .04       0
Bank Sta=752.92,792.73
XS Rating Curve= 0 ,0
Exp/Cntr=0.3,0.1

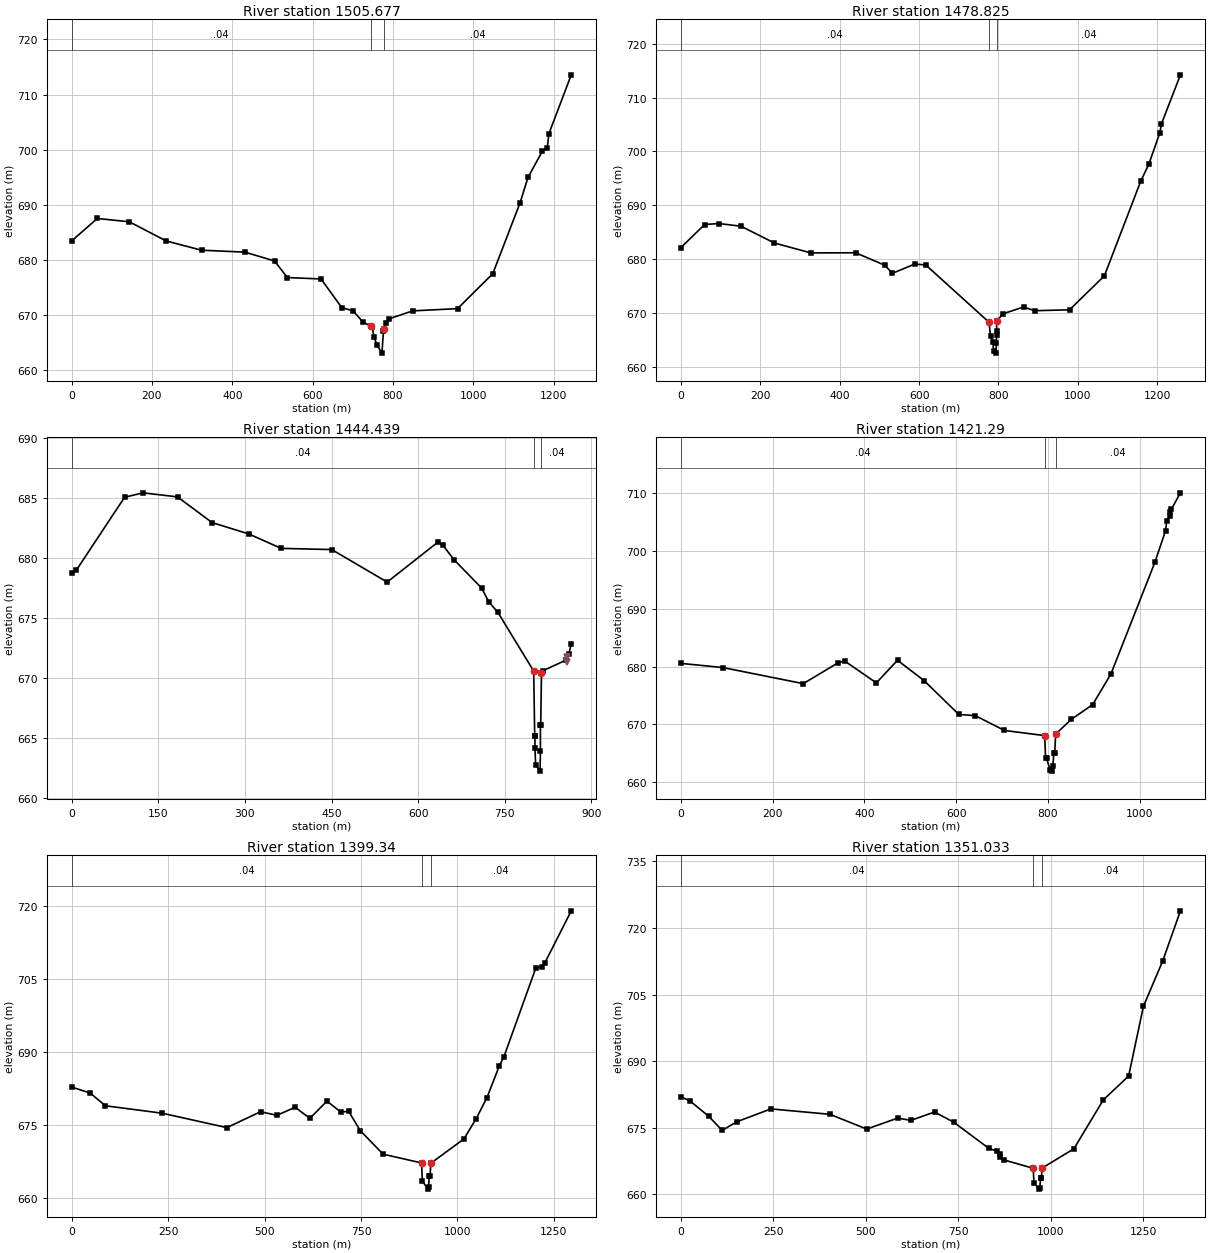
Type RM Length L Ch R = 1 ,1505.677,32.84,26.85,26.36
XS GIS Cut Line= 6
261587.6047319021515225.29357957261535.0300319021514768.97997957
261503.5000319021514471.31997957261495.9300319021514451.84997957
261450.9400319021514025.52997957261447.2726717371513989.85534834
#Sta/Elev= 30
       0  683.46   63.91  687.54  143.79  686.93  235.66  683.45  323.53  681.78
  431.37  681.43  505.22  679.83  537.15  676.82  620.96  676.57  672.85  671.35
  700.78  670.79  724.73  668.81  744.69     668  748.68  667.81  752.67  666.06
  760.65  664.53  772.62  663.12  776.42  667.09  777.44  667.47  782.24  668.67
  789.72  669.33  849.35  670.78     961  671.19 1048.73  677.53 1116.52  690.36
 1136.46  695.01 1172.35  699.75 1184.31  700.35  1188.3  702.88 1244.09  713.58
#Mann= 3 , 0 , 0
       0     .04       0  744.69     .03       0  777.44     .04       0
Bank Sta=744.69,777.44
XS Rating Curve= 0 ,0
Exp/Cntr=0.3,0.1

Type RM Length L Ch R = 1 ,1478.825,33.87,34.39,26.87
XS GIS Cut Line= 6
261603.4797319021515223.17697957261558.2900319021514792.37997957
261525.3100319021514450.87997957261514.4300319021514446.34997957
261469.6100319021514020.47997957261465.4313372161513978.76013791
#Sta/Elev= 30
       0  682.13   59.88  686.43   95.81  686.62  151.71  686.11  235.54     683
  327.37  681.16  440.21  681.18   513.1  678.89  533.03  677.37  588.82  679.08
  616.72  678.93  776.14  668.28  780.03  665.64  785.73 664.681  787.63   662.9
  793.32  662.54 794.852  664.34 795.194  665.87 795.272  666.66 795.313  668.46
  811.19  669.85  863.09   671.1  891.04  670.42  978.87  670.59  1066.7   676.9
 1158.52  694.54 1178.49  697.61 1206.43   703.5 1210.42  705.13  1258.2  714.24
#Mann= 3 , 0 , 0
       0     .04       0  776.14     .03       0 795.313     .04       0
Bank Sta=776.14,795.313
XS Rating Curve= 0 ,0
Exp/Cntr=0.3,0.1

Type RM Length L Ch R = 1 ,1444.439,21.47,23.15,23.89
XS GIS Cut Line= 6
261627.8214319021515224.23527957261578.0600319021514762.51997957
261574.0700319021514724.76997957261542.7000319021514428.71997957
261534.5000319021514415.65997957261529.2889391651514366.28253352
#Sta/Elev= 30
       0  678.74    7.97  678.97   91.68  685.06  123.57  685.43  183.36  685.09
  243.15  682.95  306.93     682  362.73   680.8  450.42   680.7  546.32  677.99
  634.23  681.32  642.23   681.1  662.21  679.85  710.16  677.48  722.15  676.35
  738.13  675.46  800.07  670.57 801.822  665.14 802.164 665.144 802.283 664.181
  803.43  662.75 811.123 662.231 811.742 663.904 811.743  666.09 812.233  666.09
  813.55  670.38  815.49  670.59  855.43  671.47  861.05  672.02  865.12  672.84
#Mann= 3 , 0 , 0
       0     .04       0  800.07     .03       0  813.55     .04       0
Levee=0,,,-1,858.06,671.33,,
Bank Sta=800.07,813.55
XS Rating Curve= 0 ,0
Exp/Cntr=0.3,0.1

Type RM Length L Ch R = 1 ,1421.29 ,24.47,21.95,20.55
XS GIS Cut Line= 6
261654.7384319021515216.31537957261621.1800319021514947.60997957
261560.5300319021514413.56997957261554.1800319021514403.44997957
261524.1400319021514154.40997957261522.2366874481514137.18360215
#Sta/Elev= 30
       0  680.55   91.59  679.83  266.81  677.05  342.87  680.67  356.89  680.96
  425.98  677.18  472.02  681.09     530  677.57  605.61  671.73  641.43  671.53
   705.1  668.97  792.66  668.08  794.65  664.14  796.64 664.144   804.6  662.16
  808.58  661.95  810.57 662.904  812.56  665.09  814.55  665.09  816.54  668.34
  850.36  670.87  897.26  673.44  937.08  678.74 1032.64  697.981056.012  703.46
 1058.49  705.151065.932  706.071066.423  706.67 1068.47  707.13 1088.38  709.99
#Mann= 3 , 0 , 0
       0     .04       0  792.66     .03       0  816.54     .04       0
Bank Sta=792.66,816.54
XS Rating Curve= 0 ,0
Exp/Cntr=0.3,0.1

Type RM Length L Ch R = 1 ,1399.34 ,50.92,48.31,48.32
XS GIS Cut Line= 6
261822.9776319021515277.54537957261703.3000319021514901.91997957
261581.1400319021514402.91997957261570.7500319021514390.75997957
261537.2000319021514116.34997957261526.8875830881514022.24027971
#Sta/Elev= 30
       0  682.77   47.79  681.55   87.61  678.93  234.95   677.4  402.27  674.45
  489.77  677.71  532.01  676.97  579.28  678.62   617.5  676.35  661.74  679.88
  697.96  677.63  718.07  677.79  748.25  673.82  807.34     669   907.1   667.2
   909.1  663.54  923.06 661.831  925.06 662.304  927.05  664.49  929.05  664.49
  931.04  667.14 1016.84  672.12 1048.76   676.3  1076.7  680.62 1108.62  687.12
 1120.59     689 1203.13  707.17 1219.12  707.45 1227.12  708.32  1295.1  718.92
#Mann= 3 , 0 , 0
       0     .04       0   907.1     .03       0  931.04     .04       0
Bank Sta=907.1,931.04
XS Rating Curve= 0 ,0
Exp/Cntr=0.3,0.1

Type RM Length L Ch R = 1 ,1351.033,36.71,32.68,26.97
XS GIS Cut Line= 6
261839.0511319021515280.89677957261705.3200319021514871.10997957
261604.5400319021514357.07997957261589.6900319021514351.17997957
261546.7600319021514076.23997957261534.425196316 1513974.9883567
#Sta/Elev= 30
       0  681.97   23.95  681.11   75.83  677.57  111.76  674.43  151.67  676.37
  243.47  679.26  403.02  678.05  502.68  674.72  586.39  677.19  622.26  676.68
  686.04  678.56  737.47   676.3  833.11  670.37 854.174  669.76  862.49     669
  864.02  668.33  873.08  667.79  953.01  665.89     955  662.64  968.99   661.2
  970.99  661.54  972.99  663.74  974.99   663.7  976.99  665.94 1062.91  670.28
 1142.84  681.32 1211.04  686.66 1251.13  702.39 1303.13  712.55 1351.13  723.86
#Mann= 3 , 0 , 0
       0     .04       0  953.01     .03       0  976.99     .04       0
Bank Sta=953.01,976.99
XS Rating Curve= 0 ,0
Exp/Cntr=0.3,0.1

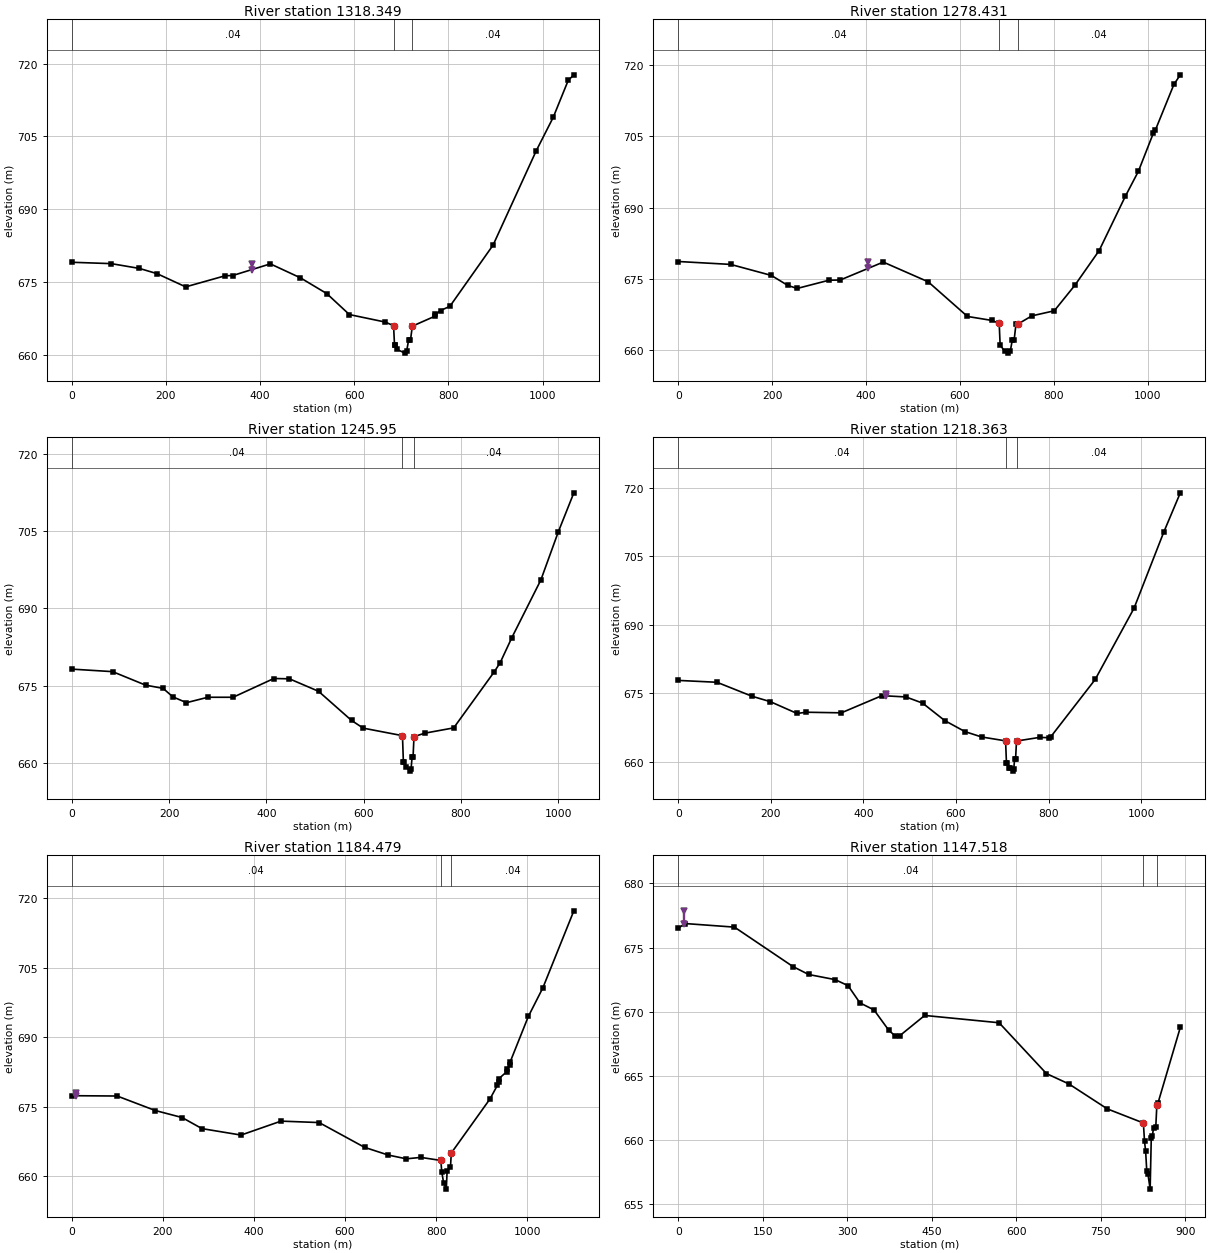
Type RM Length L Ch R = 1 ,1318.349,26.63,39.92,47.04
XS GIS Cut Line= 6
261759.9079943211515009.85917075261711.7731319021514868.12077957
261617.5700319021514326.76997957261598.8200319021514319.98997957
261554.6700319011514055.96997957261544.9232054921513977.07357632
#Sta/Elev= 30
       0  679.0683.83008  678.78143.7001  677.79  180.92  676.72  241.91  673.99
325.8301  676.28341.8201  676.33421.7502  678.73485.6902  675.85541.6401   672.6
589.5901  668.28665.5001  666.74683.4302  665.99  685.42  662.04  687.41 662.044
   691.4 661.081707.3501 660.331711.3401 660.804715.3201  662.99719.3102  662.99
723.3002  665.89771.1501  667.94772.3331  668.31783.1201  669.11803.0601  669.98
894.7802   682.6986.5001  702.06 1022.39  708.91 1054.29  716.54 1066.31   717.7
#Mann= 3 , 0 , 0
       0     .04       0683.4302     .03       0723.3002     .04       0
Levee=-1,381.7801,678.7,0,,,Levee 3,
Bank Sta=683.4302,723.3002
XS Rating Curve= 0 ,0
Exp/Cntr=0.3,0.1

Type RM Length L Ch R = 1 ,1278.431,33.5,32.48,31.51
XS GIS Cut Line= 6
261769.9083231491514992.50484725261728.1330319021514867.74867957
261639.5200319021514304.24997957261634.0000319021514293.65997957
261560.7700319021513999.57997957 261554.225584411513947.79570609
#Sta/Elev= 30
       0  678.67111.6299  678.06  198.23  675.75  233.29  673.65  253.22  673.01
  320.99  674.74  344.91  674.78  436.59  678.55532.2599  674.41  615.97  667.13
  667.77   666.3  683.53  665.68   685.5  661.14  695.36 659.794  703.28 659.431
  707.26 659.904  711.24  662.09  715.22  662.09   719.2  665.48723.1799  665.53
 753.203  667.26800.8099  668.32  844.59  673.67  896.34  680.96952.0699  692.35
979.9399  697.61 1011.78  705.62 1015.76  706.18 1055.57  715.85 1069.22  717.87
#Mann= 3 , 0 , 0
       0     .04       0  683.53     .03       0723.1799     .04       0
Levee=-1,404.7,678.54,0,,,Levee 3,
Bank Sta=683.53,723.1799
XS Rating Curve= 0 ,0
Exp/Cntr=0.3,0.1

Type RM Length L Ch R = 1 ,1245.95 ,25.14,27.59,28.59
XS GIS Cut Line= 6
261787.7054628311514972.02131232261754.7451319011514869.22127957
261669.7100319011514291.88997957261661.4200319011514275.98997957
261575.2500319021513978.72997957261573.3919867481513965.33965664
#Sta/Elev= 30
       0  678.2283.95996  677.73  151.83  675.11  187.73  674.49  207.91  672.84
  235.87  671.71   279.8  672.76  331.72  672.76  415.59   676.4  447.55  676.34
  507.45  673.92  575.35  668.26599.3199  666.77680.0599  665.31  681.95  660.14
  683.84 660.144  687.83 659.181695.7999 658.431  697.79 658.904  699.78  661.09
  701.77  661.09  703.77  665.12725.6799  665.79785.4399  666.82  869.11  677.74
881.0699  679.49  904.97  684.33  964.74  695.54  1000.6  704.87 1032.47  712.42
#Mann= 3 , 0 , 0
       0     .04       0680.0599     .03       0  703.77     .04       0
Bank Sta=680.0599,703.77
XS Rating Curve= 0 ,0
Exp/Cntr=0.3,0.1

Type RM Length L Ch R = 1 ,1218.363,33.56,33.88,33.82
XS GIS Cut Line= 6
261808.1781234221514980.56248348261771.6567319021514868.73637957
261759.0000319021514778.37997957261692.7000319021514278.72997957
261575.0300319021513955.57997957261571.4669964981513927.91784222
#Sta/Elev= 30
       0  677.8483.73993  677.43  159.28  674.38  198.95  673.19  256.72  670.61
  276.65  670.88   352.4  670.75440.1099  674.51491.9399  674.22527.8199  672.88
575.6699  669.06  619.52  666.64   655.4  665.47707.1899  664.62  709.14  659.71
  711.09 659.714714.9999 658.751  716.95  658.76722.8099 658.001724.8099 658.474
726.8099  660.66728.8099  660.66730.7999  664.58780.7899  665.38800.7799  665.31
804.7799   665.5900.7499  678.04  984.73  693.63 1048.71  710.21  1084.7  718.86
#Mann= 3 , 0 , 0
       0     .04       0707.1899     .03       0730.7999     .04       0
Levee=-1,448.2999,674.96,0,,,,
Bank Sta=707.1899,730.7999
XS Rating Curve= 0 ,0
Exp/Cntr=0.3,0.1

Type RM Length L Ch R = 1 ,1184.479,37.1,36.96,38.45
XS GIS Cut Line= 6
261851.2349759031515077.62912451261777.9526319021514866.77637957
261724.7600319021514269.51997957261721.0700319021514256.01997957
261623.5500319021514028.15997957261621.5424154371514010.57281114
#Sta/Elev= 30
       0  677.3699.65002  677.29  183.36  674.16  242.07  672.65285.9401  670.25
371.6801  668.86  459.42  671.87  543.17  671.56  642.87  666.21  694.72  664.55
   734.6  663.73   766.5  664.04  810.37  663.38  812.37 660.924  816.36 658.608
  822.34 657.189824.1801 661.162  831.53 661.992  833.36 664.992  918.51  676.69
   934.5   679.6937.6801  680.32 937.976  681.05  954.61   682.5 955.536  683.22
 962.335  683.94 962.735  684.68 1002.46  694.46 1034.45  700.66 1102.41  717.27
#Mann= 3 , 0 , 0
       0     .04       0  810.37     .03       0  833.36     .04       0
Levee=-1,9.359985,677.97,0,,,,
Bank Sta=810.37,833.36
XS Rating Curve= 0 ,0
Exp/Cntr=0.3,0.1

Type RM Length L Ch R = 1 ,1147.518,23.75,26.08,27.63
XS GIS Cut Line= 6
261888.1427501461515078.52292873261800.8000319021514840.71997957
261762.4200319011514280.59997957261761.2000319021514262.66997957
261755.9300319021514243.39997957261744.8141119431514206.94955212
#Sta/Elev= 30
       0  676.5111.97009  676.8899.74011   676.6203.4701  673.53  231.39  672.91
278.3301  672.51301.3401  672.04322.3401   670.7347.3201  670.15373.3301  668.58
385.3201   668.1393.3201  668.15437.3201  669.72569.3101  669.15   653.3  665.19
   693.3  664.38761.3002  662.44  825.29 661.342  827.29 659.924  829.29 659.135
  831.29 657.608  833.29 657.399  837.29 656.189  839.29 660.162  841.29 660.333
  843.29 660.971847.2502 660.992849.2101  662.74  851.17  662.89890.8201  668.79
#Mann= 3 , 0 , 0
       0     .04       0  825.29     .03       0849.2101     .04       0
Levee=-1,11.07007,677.87,0,,,,
Bank Sta=825.29,849.2101
XS Rating Curve= 0 ,0
Exp/Cntr=0.3,0.1

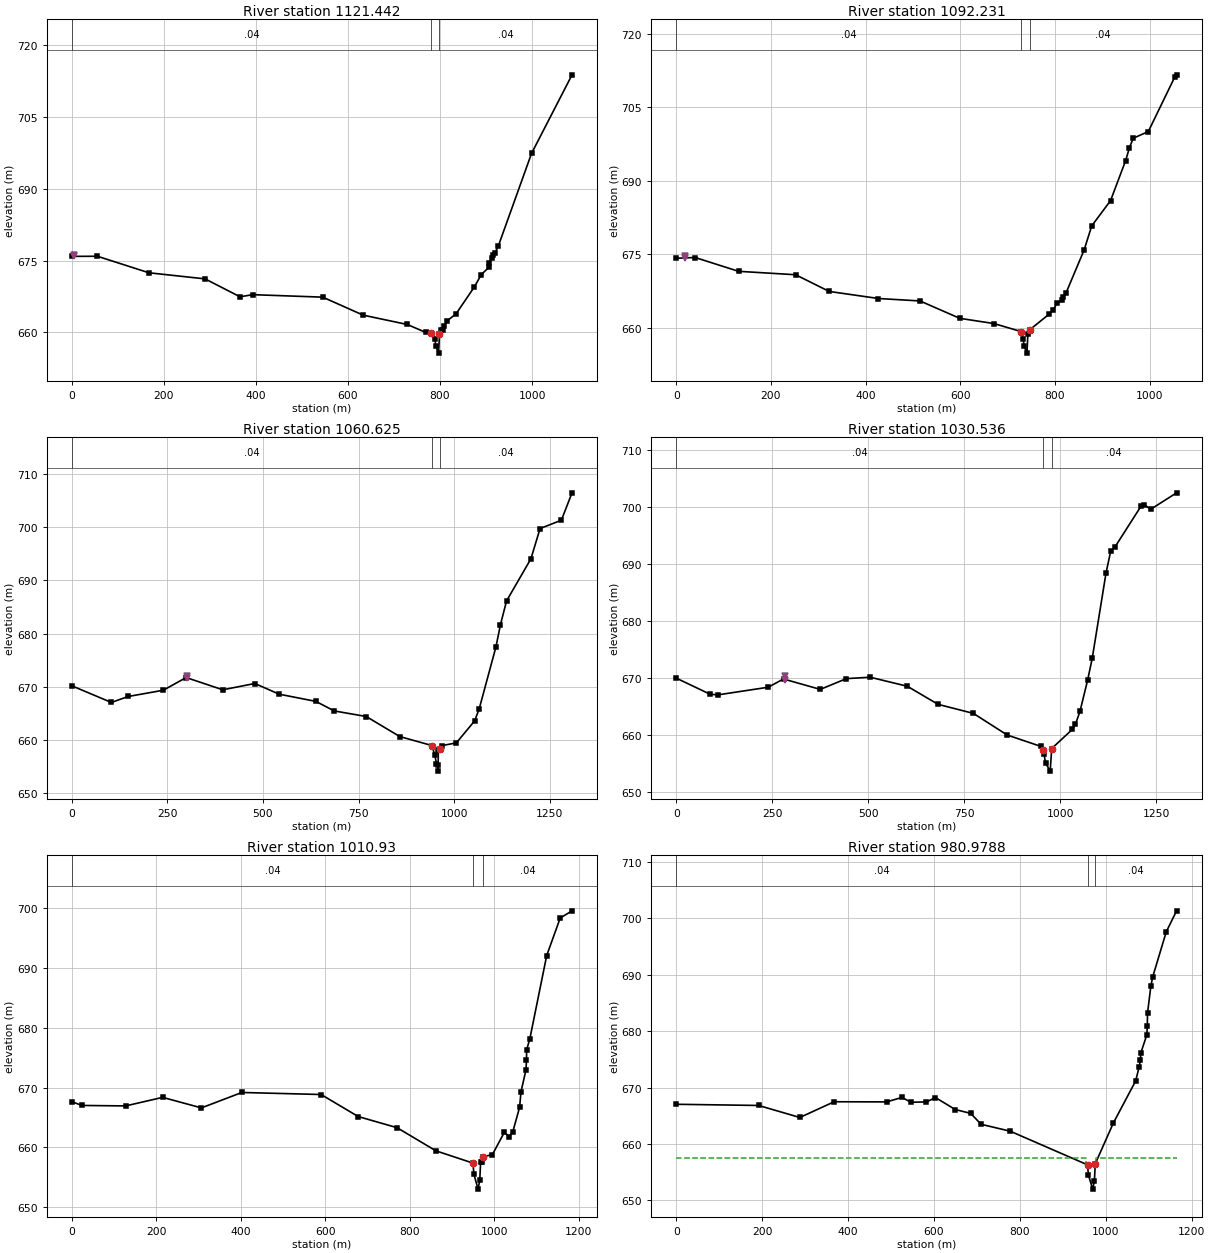
Type RM Length L Ch R = 1 ,1121.442,30.73,29.21,29.35
XS GIS Cut Line= 6
261898.8017490541515019.28936079261818.1900319021514808.35997957
261783.7200319021514246.15997957261770.6200319021514175.36997957
261768.7900319021514165.53997957261729.4982746451513953.33035309
#Sta/Elev= 30
       0   675.955.95996  675.92  167.86  672.47289.7101   671.2   365.6  667.46
393.5601   667.9  545.34  667.38  633.22  663.62  729.08  661.67  769.02  660.02
781.0001  659.98  788.99 658.635  790.99 657.108  796.98 655.689  798.97 659.662
  802.97 660.471  806.96 660.492  808.96  661.34814.9501  662.39  834.92  663.89
  874.91  669.55889.5701  672.07  906.38  673.63 907.306   674.6914.1051  675.57
  914.61  676.25   918.9  676.51   926.9   678.1  998.89   697.4 1086.88  713.82
#Mann= 3 , 0 , 0
       0     .04       0781.0001     .03       0  798.97     .04       0
Levee=-1,4.240112,676.25,0,,,,
Bank Sta=781.0001,798.97
XS Rating Curve= 0 ,0
Exp/Cntr=0.3,0.1

Type RM Length L Ch R = 1 ,1092.231,31.96,31.61,31.41
XS GIS Cut Line= 6
 261920.565171311514964.37307184261850.4400319021514756.74997957
261847.0000319021514708.92997957261813.9100319021514247.42997957
261810.4700319021514231.86997957261771.1340170021513923.33286668
#Sta/Elev= 30
       0  674.1639.83997  674.31  131.49  671.49252.1101  670.79323.0501  667.38
  426.95  665.94514.8701  665.44  598.79  661.89670.7301  660.83728.6701  659.18
732.6701 657.735734.6701 656.208  740.66 654.789  742.66 658.762  746.66 659.571
  787.76  662.76  795.73  663.54803.7161  664.93  815.16  665.59816.0861  666.27
 822.885     667  861.48  675.87877.4201  680.76  917.27  685.93  949.15  694.11
  957.12  696.72965.0901  698.65996.9701  700.02 1052.76  711.14 1056.74   711.6
#Mann= 3 , 0 , 0
       0     .04       0728.6701     .03       0  746.66     .04       0
Levee=-1,19.46008,674.67,0,,,,
Bank Sta=728.6701,746.66
XS Rating Curve= 0 ,0
Exp/Cntr=0.3,0.1

Type RM Length L Ch R = 1 ,1060.625,28.94,30.09,32
XS GIS Cut Line= 6
262039.7353319021515163.99507957261894.1700319011514707.93997957
261844.5600319021514239.68997957261840.6700319011514222.03997957
261808.5100319021513917.23997957 261804.946632661513883.55632707
#Sta/Elev= 30
       0  670.23  103.72  667.09  147.61  668.21  239.36  669.38   299.2  671.77
  394.95  669.47  478.72  670.65  542.57  668.64  638.34  667.29  686.22   665.5
  770.03  664.45  857.82  660.68  941.62     659   949.6 657.135  953.59 655.608
  957.24 655.399 957.646 654.189 958.632 658.162 962.836 658.333   966.8 658.971
 1005.51  659.49 1053.28  663.62 1065.22  665.86    1109   677.5 1120.94  681.72
 1136.87  686.17 1200.55  694.08 1224.44  699.76 1280.16  701.33 1308.03  706.47
#Mann= 3 , 0 , 0
       0     .04       0  941.62     .03       0 962.836     .04       0
Levee=-1,300.41,672.13,0,,,,
Bank Sta=941.62,962.836
XS Rating Curve= 0 ,0
Exp/Cntr=0.3,0.1

Type RM Length L Ch R = 1 ,1030.536,19.96,19.61,19.61
XS GIS Cut Line= 6
262072.0145319021515171.40337957261922.7400319021514706.14997957
261873.0400319021514237.01997957261872.8300319021514234.95997957
261872.1300319011514215.30997957261838.4999339741513896.63191339
#Sta/Elev= 30
       0  669.94   87.75  667.12  107.69  666.99  239.32  668.34  279.21  669.79
  374.94  667.96  442.74  669.85  504.61   670.1  601.58  668.51  681.55  665.33
  773.51  663.74  861.48  659.94  949.45  657.93  953.45 657.324  957.44 656.535
  961.44 655.008  973.44 653.589  977.44 657.562 1031.07  660.93 1039.05   661.8
 1051.03   664.1 1070.99  669.62 1082.97  673.45  1118.9  688.47 1130.88  692.24
 1142.86  693.08 1210.73  700.26 1218.71  700.45 1234.68  699.61 1302.55  702.52
#Mann= 3 , 0 , 0
       0     .04       0  953.45     .03       0  977.44     .04       0
Levee=-1,284.36,670.29,0,,,,
Bank Sta=953.45,977.44
XS Rating Curve= 0 ,0
Exp/Cntr=0.3,0.1

Type RM Length L Ch R = 1 ,1010.93 ,27.87,29.95,30.73
XS GIS Cut Line= 6
262097.4146319021515166.11167957261942.5000319021514707.11997957
261896.2000319021514270.14997957261892.4200319011514234.38997957
261891.7600319021514215.84997957261870.1638752411514011.18639978
#Sta/Elev= 30
       0  667.65   23.92     667  127.59  666.92   215.3  668.35     307  666.59
  402.69  669.17  590.29  668.83  678.18  665.14  770.06  663.28  861.94  659.41
  949.82  657.35  951.82   655.5  961.81     653   965.8   654.5   967.8   657.5
  971.79   657.5  973.79  658.41  995.76  658.79 1023.72  662.48 1035.71   661.8
  1043.7  662.53 1060.09   666.7  1063.3  669.27  1075.3     673  1076.3  674.65
  1076.8  676.32  1084.3  678.16  1124.2  692.08 1156.17  698.36 1184.15  699.56
#Mann= 3 , 0 , 0
       0     .04       0  949.82     .03       0  973.79     .04       0
Bank Sta=949.82,973.79
XS Rating Curve= 0 ,0
Exp/Cntr=0.3,0.1

Type RM Length L Ch R = 1 ,980.9788,27.29,26.98,26.62
XS GIS Cut Line= 6
262121.7563319021515158.70337957261968.9600319011514697.85997957
261920.2900319021514238.43997957261920.0700319021514236.45997957
261922.9600319011514221.32997957261901.9836273131514022.49928846
#Sta/Elev= 30
       0  667.03  191.81  666.82  287.71  664.69  367.63  667.48  489.51  667.45
  525.51  668.24  546.51  667.39  582.51  667.45  603.51  668.22  649.51   666.1
  685.51  665.42  709.51  663.49  777.51  662.26   957.5   656.3   959.5   654.5
   969.5     652   973.5   653.5   975.5   656.5  1017.5   663.7  1069.5  671.17
  1077.5  673.61 1080.61  674.89 1081.61  676.14 1095.61  679.36 1096.61  680.89
 1097.11  683.18 1104.89  687.94 1108.89  689.52 1140.87  697.61 1164.85   701.3
#Mann= 3 , 0 , 0
       0     .04       0   957.5     .03       0   975.5     .04       0
#XS Ineff= 2 , 0
       0   953.5  657.57   977.5       0  657.57
Permanent Ineff=
       F       F
Bank Sta=957.5,975.5
XS Rating Curve= 0 ,0
Exp/Cntr=0.3,0.1

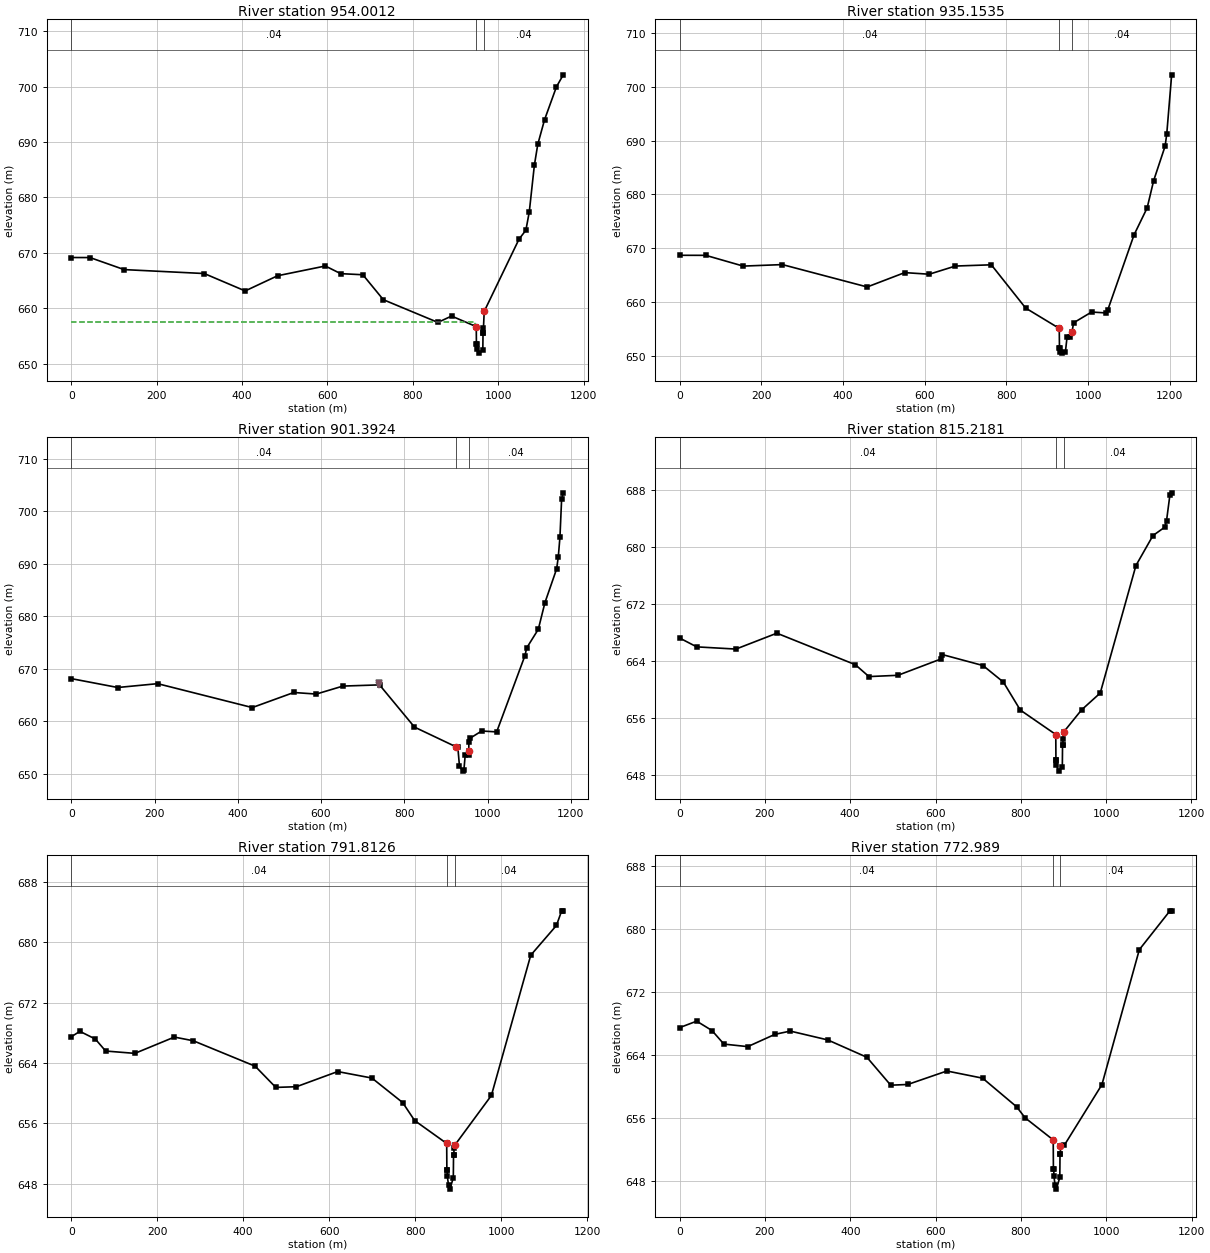
Type RM Length L Ch R = 1 ,954.0012,20.73,18.85,17.72
XS GIS Cut Line= 6
262146.0980319021515158.70337957261995.7700319021514697.34997957
261947.3700319021514240.46997957261947.1500319021514238.47997957
261949.8900319021514224.13997957261929.8304593861514034.05401014
#Sta/Elev= 30
       0  669.15   43.93  669.14   123.8  666.97   311.5  666.26  407.35  663.12
  483.23  665.86   595.1  667.62  631.05  666.24  682.99  666.04  730.93  661.54
  858.78  657.44  890.74  658.59  948.64  656.68  948.97   653.5  949.97   653.5
  949.97   652.7  955.97   651.9  963.97   652.5  964.47   655.5  965.39   655.5
  965.47  656.41  967.25  659.43 1048.88  672.48 1064.81  674.07 1072.78  677.37
 1084.72   685.8 1092.69  689.56 1108.62  694.02 1136.49  699.96 1152.42  702.11
#Mann= 3 , 0 , 0
       0     .04       0  948.64     .03       0  967.25     .04       0
#XS Ineff= 2 , 0
       0  946.67  657.57               0
Permanent Ineff=
       F       F
Bank Sta=948.64,967.25
XS Rating Curve= 0 ,0
Exp/Cntr=0.3,0.1

Type RM Length L Ch R = 1 ,935.1535,26.11,33.76,45.22
XS GIS Cut Line= 6
262170.4397319021515154.46997957262009.0900319021514655.02997957
261965.4500319021514243.11997957261968.1400319021514229.04997957
261966.4600319011514213.21997957261941.8141842051513979.59055843
#Sta/Elev= 30
       0  668.69   63.86  668.68  155.66  666.68  251.45  666.96     459   662.8
  550.88  665.47  610.87  665.17  674.86  666.69  762.85  666.92  846.84  658.88
  928.62  655.12  929.12  655.16  929.62   651.5  930.04   651.5  930.12   650.7
  936.26   650.5  944.26   650.8  948.26   653.5  956.26   653.5  960.26  654.41
  964.26  656.14 1008.26  658.14 1044.26  657.97 1048.26  658.61 1112.26   672.5
 1144.26   677.5 1160.25  682.59 1188.25  688.99 1192.25  691.26 1204.25  702.24
#Mann= 3 , 0 , 0
       0     .04       0  928.62     .03       0  960.26     .04       0
Bank Sta=928.62,960.26
XS Rating Curve= 0 ,0
Exp/Cntr=0.3,0.1

Type RM Length L Ch R = 1 ,901.3924,83.94,86.17,86.14
XS GIS Cut Line= 6
262195.8397319021515156.58667957262031.2100319011514652.23997957
261992.2300319021514284.34997957261989.5000319021514258.48997957
262005.0500319021514243.73997957261980.4894620041514011.04457911
#Sta/Elev= 30
       0  668.11  111.69  666.42  207.43  667.15   434.8   662.6  534.54  665.47
  588.53  665.17  652.53  666.69  740.51  666.92   824.5  658.88  924.49  655.12
  928.49  655.16  932.49   651.5  940.28   650.5  943.28   650.8  946.28   653.5
  954.28   653.5  954.78  654.41  955.28  656.14  957.97  656.76  985.92  658.14
 1021.92  657.97 1089.92   672.5 1093.92  673.94 1121.92   677.5 1137.92  682.59
 1165.92  688.99 1169.92  691.26 1173.92  695.05 1177.91  702.24 1181.91  703.48
#Mann= 3 , 0 , 0
       0     .04       0  924.49     .03       0  954.78     .04       0
Levee=-1,740.05,667.34,0,,,,
Bank Sta=924.49,954.78
XS Rating Curve= 0 ,0
Exp/Cntr=0.3,0.1

Type RM Length L Ch R = 1 ,815.2181,26.47,23.41,21.98
XS GIS Cut Line= 6
262255.1065319021515170.34507957262079.7300319021514579.98997957
262065.4900319021514445.49997957262052.0700319021514318.91997957
262062.4500319021514306.54997957262082.3090777381514048.11270176
#Sta/Elev= 30
       0  667.18   39.99  665.94  131.97  665.63  227.95  667.86   411.9  663.44
  443.89  661.77  511.88  661.95  611.85  664.22  615.85  664.86  711.32  663.32
  759.05     661  798.83  657.07  881.99  653.64  882.34   650.1  883.34   650.1
  883.34   649.3  889.34   648.5  897.34   649.1  897.84   652.1  898.76   652.1
  898.84  653.01   900.5  653.99  942.38  657.09  986.24  659.46 1069.98  677.36
 1109.86  681.56 1137.77  682.75 1141.76  683.67 1149.74  687.32 1153.72  687.56
#Mann= 3 , 0 , 0
       0     .04       0  881.99     .03       0   900.5     .04       0
Bank Sta=881.99,900.5
XS Rating Curve= 0 ,0
Exp/Cntr=0.3,0.1

Type RM Length L Ch R = 1 ,791.8126,17.47,18.82,18.89
XS GIS Cut Line= 6
262278.3899319021515185.16177957262099.4500319021514562.74997957
262074.7400319021514329.50997957262082.8500319021514314.12997957
262084.6900319021514290.30997957 262101.617820731514070.01916705
#Sta/Elev= 30
       0  667.49   19.99  668.21   55.97  667.19   79.95   665.6  147.91  665.29
  239.86  667.45  283.84  666.96  427.75  663.59  475.72  660.78  523.69  660.87
  619.64  662.88  699.26  662.02  770.82  658.77  798.65  656.39  873.24  653.35
  873.63   649.8  874.63   649.8  874.63     649  877.63   647.8  880.63   647.3
  888.63   648.8  889.13   651.8  890.05   651.8  890.13  652.71  891.62  653.09
  977.17  659.71 1068.74   678.3 1128.47  682.24 1140.41  684.14 1144.39  684.18
#Mann= 3 , 0 , 0
       0     .04       0  873.24     .03       0  891.62     .04       0
Bank Sta=873.24,891.62
XS Rating Curve= 0 ,0
Exp/Cntr=0.3,0.1

Type RM Length L Ch R = 1 ,772.989 ,19.26,16.76,13.37
XS GIS Cut Line= 6
262293.2066319021515195.74507957262113.8700319021514564.53997957
262090.1500319021514340.62997957262100.6600319021514320.72997957
262105.0800319021514263.08997957  262119.74888311514072.34514375
#Sta/Elev= 30
       0  667.48   39.89   668.3   75.79  667.11  103.71  665.39  159.56  665.07
  223.38  666.63  259.28  667.04  347.04  665.92  438.79  663.72  494.63  660.18
  534.52  660.27  626.27  661.98  709.98  661.07  789.68  657.44   809.6  656.04
  875.44  653.24  875.86   649.5  876.86   649.5  876.86   648.7  879.86   647.5
  882.86     647  890.86   648.5  891.36   651.5  892.28   651.5  892.36  652.41
  901.85   652.6  989.55  660.25 1077.24  677.37 1148.99  682.29 1152.98  682.28
#Mann= 3 , 0 , 0
       0     .04       0  875.44     .03       0  892.36     .04       0
Bank Sta=875.44,892.36
XS Rating Curve= 0 ,0
Exp/Cntr=0.3,0.1