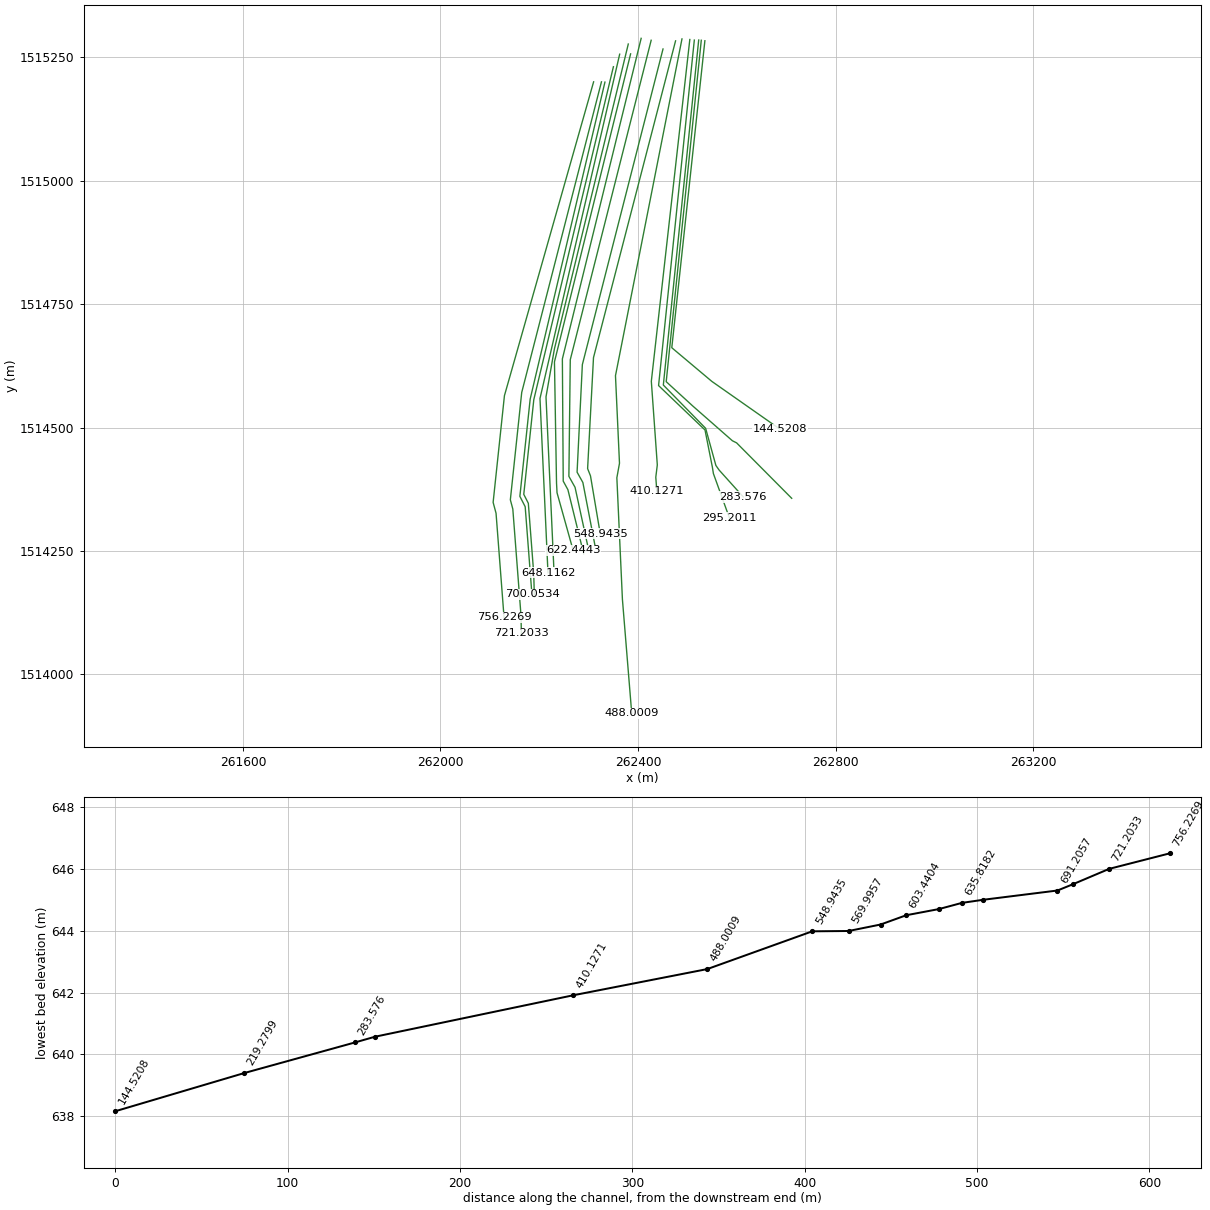
HEC-RAS study amss1_V6.prj: amss1_V6

--- amss1_V6.g01 (geometry) --- (continued)

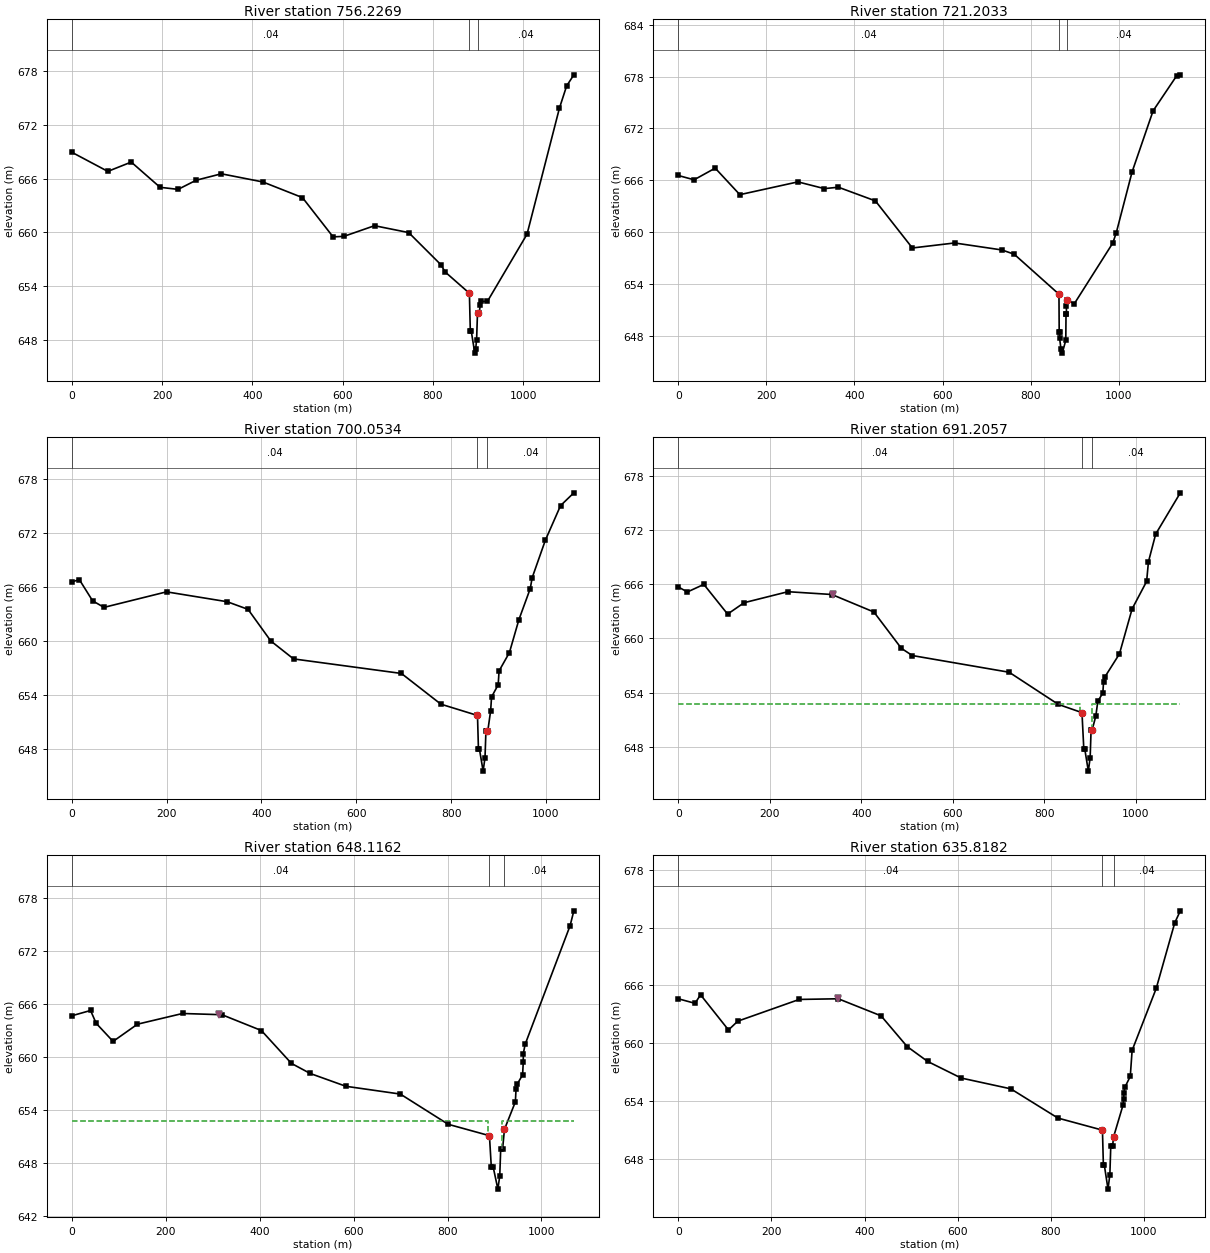
Type RM Length L Ch R = 1 ,756.2269,37.82,35.02,35.39
XS GIS Cut Line= 6
262310.1400319021515199.97847957262129.5500319021514564.44997957
262106.6600319021514348.40997957262112.0700319021514328.19997957
262112.5700319021514326.36997957 262128.767756351514115.61001686
#Sta/Elev= 30
       0  668.95   79.84  666.81  131.74  667.85  195.61  665.03  235.53   664.8
  275.45  665.82  331.34  666.54  423.16  665.63  510.99  663.88  578.85  659.49
   602.8  659.55  670.57  660.74  746.31  659.97  818.06  656.36   826.6  655.59
  880.76  653.19  882.76     649  884.75     649  892.73   646.5  894.73     647
  896.72     648  898.71     651   902.7     651   904.7  651.91  906.69  652.27
  920.65  652.28 1008.41  659.79 1080.21  673.88 1096.16  676.36 1112.12   677.6
#Mann= 3 , 0 , 0
       0     .04       0  880.76     .03       0  898.71     .04       0
Bank Sta=880.76,898.71
XS Rating Curve= 0 ,0
Exp/Cntr=0.3,0.1

Type RM Length L Ch R = 1 ,721.2033,20.43,21.15,23.15
XS GIS Cut Line= 6
262326.0150319021515199.97847957262164.5600319021514570.97997957
262141.5300319021514353.59997957262146.5300319021514334.92997957
262162.9700319021514121.02997957262163.9251996281514083.05283058
#Sta/Elev= 30
       0  666.56   35.97  666.06   83.92  667.41  139.87  664.34  271.74  665.82
  331.69  665.04  363.66   665.2  447.58  663.62   531.5  658.17  627.41  658.75
  734.83  657.94  762.65  657.45  864.33  652.82  864.84   648.5  865.84   648.5
  865.84   647.7  868.84   646.5  871.84     646  879.84   647.5  880.34   650.5
  881.26   650.5  881.34  651.41  881.51  652.16  899.23  651.72  986.63  658.75
  994.58  659.96 1030.33  666.97    1078  674.04 1131.83  678.12 1139.82  678.21
#Mann= 3 , 0 , 0
       0     .04       0  864.33     .03       0  881.51     .04       0
Bank Sta=864.33,881.51
XS Rating Curve= 0 ,0
Exp/Cntr=0.3,0.1

Type RM Length L Ch R = 1 ,700.0534,8.23,8.85,8.94
XS GIS Cut Line= 6
262333.0706319021515199.44927957262181.6800319021514557.61997957
262160.8100319021514360.66997957262171.5700319021514339.58997957
262173.1100319021514319.66997957262185.1805680041514162.57949821
#Sta/Elev= 30
       0  666.58   15.99  666.83   43.96  664.47   67.94  663.74  199.83  665.47
  327.72  664.37  371.69  663.52  419.65     660   467.6     658   695.1  656.38
  778.28  652.96  855.52   651.7   857.5     648  859.48     648   867.4   645.5
  871.36     647  873.34     650  875.32     650   877.3     650  883.26  652.23
  885.16  653.76  899.16  655.12     901  656.66  922.85  658.71  942.82  662.37
   966.8  665.84  970.79  667.04  998.76  671.24 1030.72  675.08 1058.69   676.5
#Mann= 3 , 0 , 0
       0     .04       0  855.52     .03       0  875.32     .04       0
Bank Sta=855.52,875.32
XS Rating Curve= 0 ,0
Exp/Cntr=0.3,0.1

Type RM Length L Ch R = 1 ,691.2057,40.06,43.09,37.84
XS GIS Cut Line= 6
262350.2156319021515230.56437957262189.0200319021514556.42997957
262168.7100319011514364.67997957262177.9400319021514346.58997957
262188.8700319021514204.41997957262190.1931020431514156.44424785
#Sta/Elev= 30
       0   665.7   19.98  665.14   55.93  665.98  107.87  662.69  143.82  663.95
   239.7  665.17  335.58  664.86  427.47  662.92   487.4   658.9  511.37   658.1
  722.96  656.25   830.3  652.69  881.99  651.78  885.96   647.8  887.95   647.8
   895.9   645.3  899.88   646.8  901.87   649.8  903.85   649.8  912.23  651.39
  916.61  653.04  927.61  653.95  929.11  655.16  932.54  655.77  963.82  658.28
  991.55  663.27 1023.24  666.31  1027.2  668.48 1043.04  671.55 1096.83  676.12
#Mann= 3 , 0 , 0
       0     .04       0  881.99     .03       0  903.85     .04       0
Levee=-1,337.1,664.94,0,,,,
#XS Ineff= 2 , 0
       0  878.01   652.7  903.85       0   652.7
Permanent Ineff=
       F       F
Bank Sta=881.99,903.85
XS Rating Curve= 0 ,0
Exp/Cntr=0.3,0.1

Type RM Length L Ch R = 1 ,648.1162,12.45,12.3,12.32
XS GIS Cut Line= 6
262362.9156319011515255.96437957262201.5500319021514558.87997957
262202.3800319011514540.92997957262203.0100319021514526.96997957
262203.7500319021514511.00997957262217.7204732531514205.81022082
#Sta/Elev= 30
       0  664.62   39.97  665.22   51.96  663.77   87.94  661.72  139.91  663.67
  235.84  664.88  319.78  664.74  403.73  662.95  467.68  659.23  507.66  658.09
  583.61  656.64  699.53  655.76  801.37  652.34  889.23  651.05  893.22   647.5
  897.21   647.5   907.2     645  911.19   646.5  913.19   649.5  917.18   649.5
  921.18  651.76  944.44  654.88  945.82  656.28  948.82  656.93  959.82  657.93
  961.24  659.36  961.32  660.32  965.11  661.37 1060.96  674.82 1068.94   676.5
#Mann= 3 , 0 , 0
       0     .04       0  889.23     .03       0  921.18     .04       0
Levee=-1,314.5,664.8,0,,,,
#XS Ineff= 2 , 0
       0  885.23   652.7  915.29       0   652.7
Permanent Ineff=
       F       F
Bank Sta=889.23,921.18
XS Rating Curve= 0 ,0
Exp/Cntr=0.3,0.1

Type RM Length L Ch R = 1 ,635.8182,13.56,13.37,13.46
XS GIS Cut Line= 6
262380.3385319021515276.52257957262230.7196319021514658.95537957
262213.7200319021514562.06997957262225.1100319021514313.49997957
262227.6500319021514257.80997957   262229.4793151514218.04583107
#Sta/Elev= 30
       0  664.62   35.97  664.15   47.96  665.03   107.9  661.39  127.89   662.3
  259.77  664.55  343.69  664.62  435.61  662.85  491.56  659.67  535.52  658.13
  607.46  656.41  714.12  655.29  815.41  652.26  910.97  651.01  912.96   647.4
  914.95   647.4  922.91   644.9  926.89   646.4  928.88   649.4  932.86   649.4
  934.85  650.31  955.37  653.64  956.72  654.26  956.72  654.88  959.72  655.51
  970.72  656.58  974.67  659.27 1026.42  665.69 1066.24  672.49 1078.18  673.73
#Mann= 3 , 0 , 0
       0     .04       0  910.97     .03       0  934.85     .04       0
Levee=-1,343,664.67,0,,,,
Bank Sta=910.97,934.85
XS Rating Curve= 0 ,0
Exp/Cntr=0.3,0.1

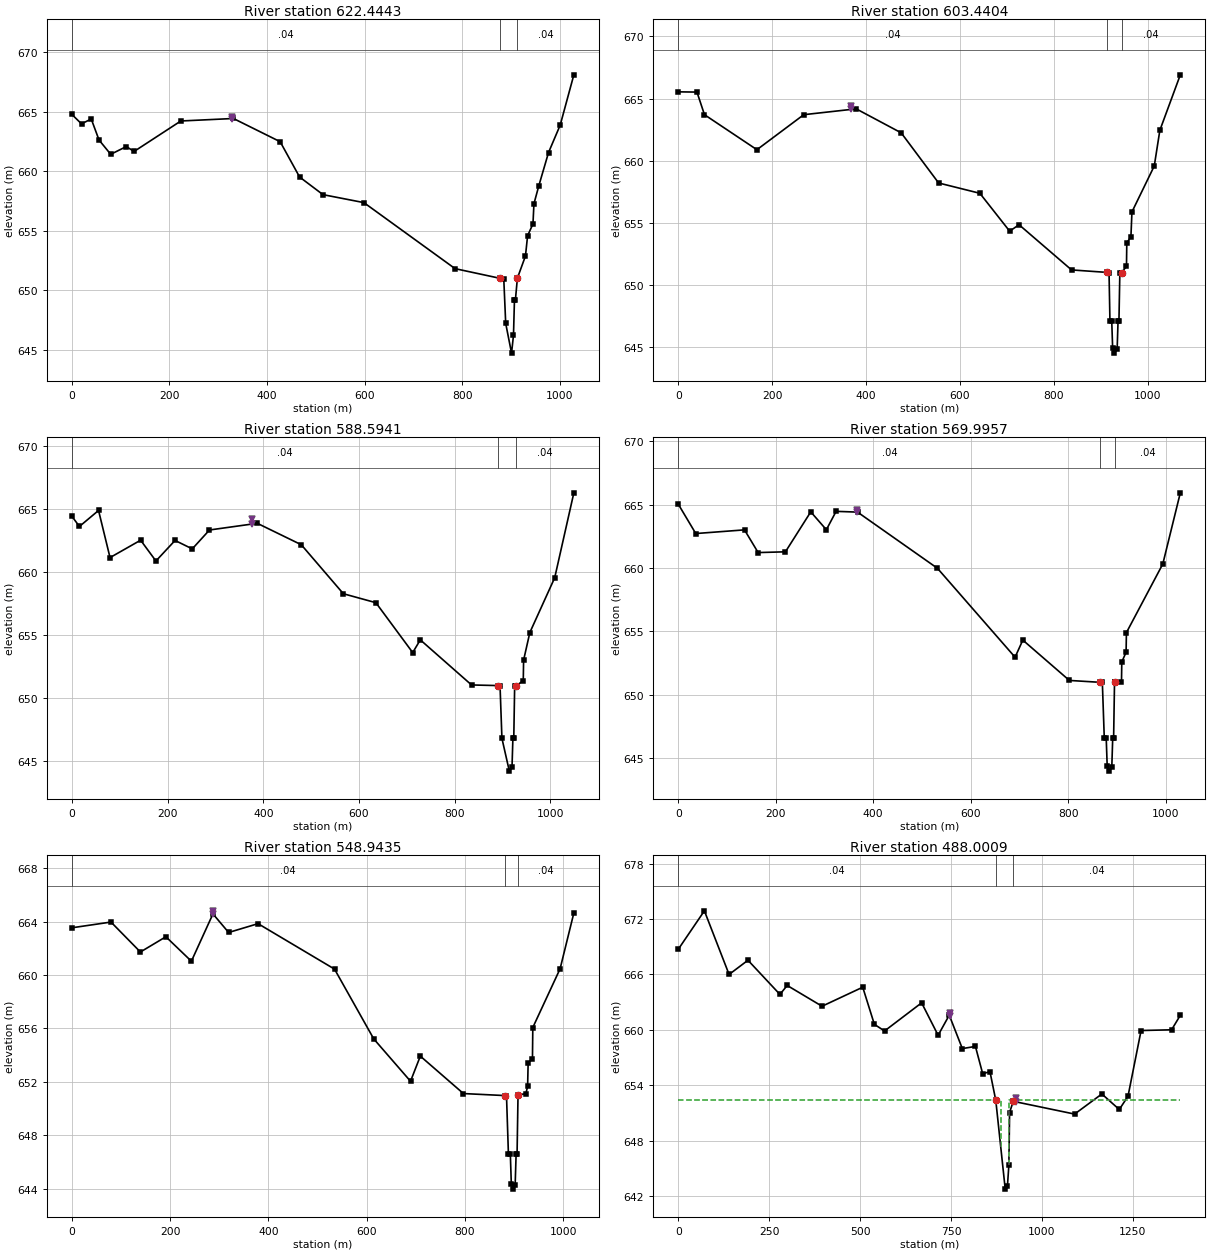
Type RM Length L Ch R = 1 ,622.4443,15.39,19,22.57
XS GIS Cut Line= 6
262385.0514319021515256.56297957262230.8500319021514632.94997957
262234.8200319021514399.50997957262235.0300319021514387.69997957
262236.0800319021514367.77997957262268.6695396251514251.20545182
#Sta/Elev= 30
       0  664.77   19.95  663.97    39.9  664.38   55.86  662.61    79.8  661.41
  111.72  662.06  127.68  661.65  223.44  664.21  331.17  664.42  426.93  662.47
  466.83   659.5  514.71  658.02   598.5  657.35  785.35   651.8   877.1  650.99
  885.08  650.97  889.06   647.2  901.03   644.7  905.02   646.2  907.02   649.2
  909.01   649.2     913     651  929.54  652.86  933.93  654.57  944.93  655.56
  946.91  657.25  956.88  658.76  976.82  661.56 1000.76  663.87 1028.68  668.09
#Mann= 3 , 0 , 0
       0     .04       0   877.1     .03       0     913     .04       0
Levee=-1,328.26,664.53,0,,,,
Bank Sta=877.1,913
XS Rating Curve= 0 ,0
Exp/Cntr=0.3,0.1

Type RM Length L Ch R = 1 ,603.4404,13.06,14.85,15.15
XS GIS Cut Line= 6
262406.4165319021515288.05177957262246.8700319021514638.92997957
262247.0500319021514614.57997957262248.6100319021514391.44997957
262258.0800319021514374.03997957262290.0719699421514244.15773128
#Sta/Elev= 30
       0  665.54   39.91  665.52   55.87   663.7  167.61  660.88  267.38   663.7
  379.12  664.17  474.89  662.24  554.71   658.2   642.5  657.37  705.98  654.32
  725.96  654.84  837.83   651.2  913.74     651  917.66  650.99  919.58   647.1
  923.42   647.1  925.34 644.898  929.18   644.5  934.94   644.8  936.86   647.1
  938.78   647.1   940.7  650.99  944.66  650.99  954.82  651.49 955.485  653.38
 964.285  653.87  966.46  655.87 1014.01  659.57  1025.9  662.44 1069.49  666.91
#Mann= 3 , 0 , 0
       0     .04       0  913.74     .03       0  944.66     .04       0
Levee=-1,367.93,664.41,0,,,,
Bank Sta=913.74,944.66
XS Rating Curve= 0 ,0
Exp/Cntr=0.3,0.1

Type RM Length L Ch R = 1 ,588.5941,18.98,18.6,18.63
XS GIS Cut Line= 6
262426.6903319011515284.14917957262262.8800319011514637.33997957
262261.4100319021514514.96997957262260.0600319021514401.13997957
262272.5400319021514378.87997957262297.9490579141514261.74304645
#Sta/Elev= 30
       0  664.44   15.98  663.62   55.94  664.89   79.91  661.15  143.83  662.53
   175.8  660.88  215.75  662.51  251.71  661.84  287.67  663.34  387.55  663.87
  479.45  662.17  567.35  658.28  635.27  657.57  712.22  653.61  728.08  654.62
  835.15  651.04  890.67  650.99  894.64  650.97   898.6   646.8  914.08   644.2
  919.65   644.5   921.5   646.8  923.35   646.8  925.21  650.99  928.92  650.99
  943.16  651.38 943.875  653.01   956.9   655.2 1008.86  659.55 1048.83  666.29
#Mann= 3 , 0 , 0
       0     .04       0  890.67     .03       0  928.92     .04       0
Levee=-1,377.4,664.22,0,,,,
Bank Sta=890.67,928.92
XS Rating Curve= 0 ,0
Exp/Cntr=0.3,0.1

Type RM Length L Ch R = 1 ,569.9957,24.39,21.05,19.74
XS GIS Cut Line= 6
262450.6792319021515266.51027957262287.3400319021514627.35997957
262281.6000319021514510.37997957262276.6700319011514409.55997957
262288.3800319011514388.65997957262312.5894189881514262.70819737
#Sta/Elev= 30
       0  665.04   35.98  662.72  135.94  663.01  163.92  661.22   219.9  661.28
  271.87  664.43  303.86  663.02  323.85  664.47  367.83  664.41  531.75  659.98
  690.97  652.97  706.88  654.32  802.37  651.14  866.03  650.99  870.01  650.99
  873.99  646.59  877.97  646.59  879.96 644.388  883.81  643.99  889.41  644.29
  891.27  646.59  893.14  646.59     895     651  896.86  650.99 909.275  650.99
 909.925   652.6 918.725  653.36  919.41  654.91  994.03  660.32 1029.96  665.93
#Mann= 3 , 0 , 0
       0     .04       0  866.03     .03       0  896.86     .04       0
Levee=-1,366.58,664.59,0,,,,
Bank Sta=866.03,896.86
XS Rating Curve= 0 ,0
Exp/Cntr=0.3,0.1

Type RM Length L Ch R = 1 ,548.9435,64.16,60.94,53.63
XS GIS Cut Line= 6
262476.0793319021515282.91447957262309.9000319021514641.53997957
262297.9800319021514416.83997957262303.8300319021514401.97997957
262313.2300319021514346.11997957262323.4988645981514285.17968646
#Sta/Elev= 30
       0  663.53   79.83  663.96  139.69  661.72  191.58  662.86  243.47  661.03
  287.37  664.57   319.3  663.18  379.17  663.84  534.83  660.44  614.66  655.22
  689.54  652.05  709.47  653.93  797.17  651.13  880.88  650.98  884.87  650.98
  888.82  646.58  892.72  646.58  894.68 644.378  898.58  643.98  902.49  644.28
  904.44  646.58  906.39  646.58  908.35  651.05  924.18  651.11 927.875  651.66
 928.925  653.41 937.725  653.73  938.44  656.07  994.03  660.47 1021.97  664.64
#Mann= 3 , 0 , 0
       0     .04       0  880.88     .03       0  908.35     .04       0
Levee=-1,287.96,664.8,0,,,,
Bank Sta=880.88,908.35
XS Rating Curve= 0 ,0
Exp/Cntr=0.3,0.1

Type RM Length L Ch R = 1 ,488.0009,76.35,77.87,78.72
XS GIS Cut Line= 6
262489.0613319021515286.87487957262354.4100319021514604.94997957
262362.5300319021514427.52997957262357.2000319021514398.19997957
262368.4700319021514152.05997957262387.3130160571513921.12988342
#Sta/Elev= 30
       0  668.72   71.91  672.89  139.82     666  191.75  667.54  279.63  663.84
  299.61  664.81  395.48  662.56  507.34  664.62 539.327   660.6 567.316  659.88
 669.274  662.93 714.626 659.416 745.243 661.592 781.229 657.974 817.214  658.21
 837.206 655.251 857.198 655.477 873.191 652.371  899.18642.7585 905.178643.0585
 909.176645.3585 911.176651.0485 921.172 652.268 1089.94 650.884 1164.89  653.06
 1212.83  651.38  1236.8  652.82 1272.75  659.93 1356.65  660.01 1380.62  661.58
#Mann= 3 , 0 , 0
       0     .04       0 873.191     .03       0 921.172     .04       0
Levee=-1,746.44,661.8,-1,927.69,652.63,,
#XS Ineff= 2 , 0
       0  887.18  652.37  909.18       0  652.37
Permanent Ineff=
       F       F
Bank Sta=873.191,921.172
XS Rating Curve= 0 ,0
Exp/Cntr=0.3,0.1

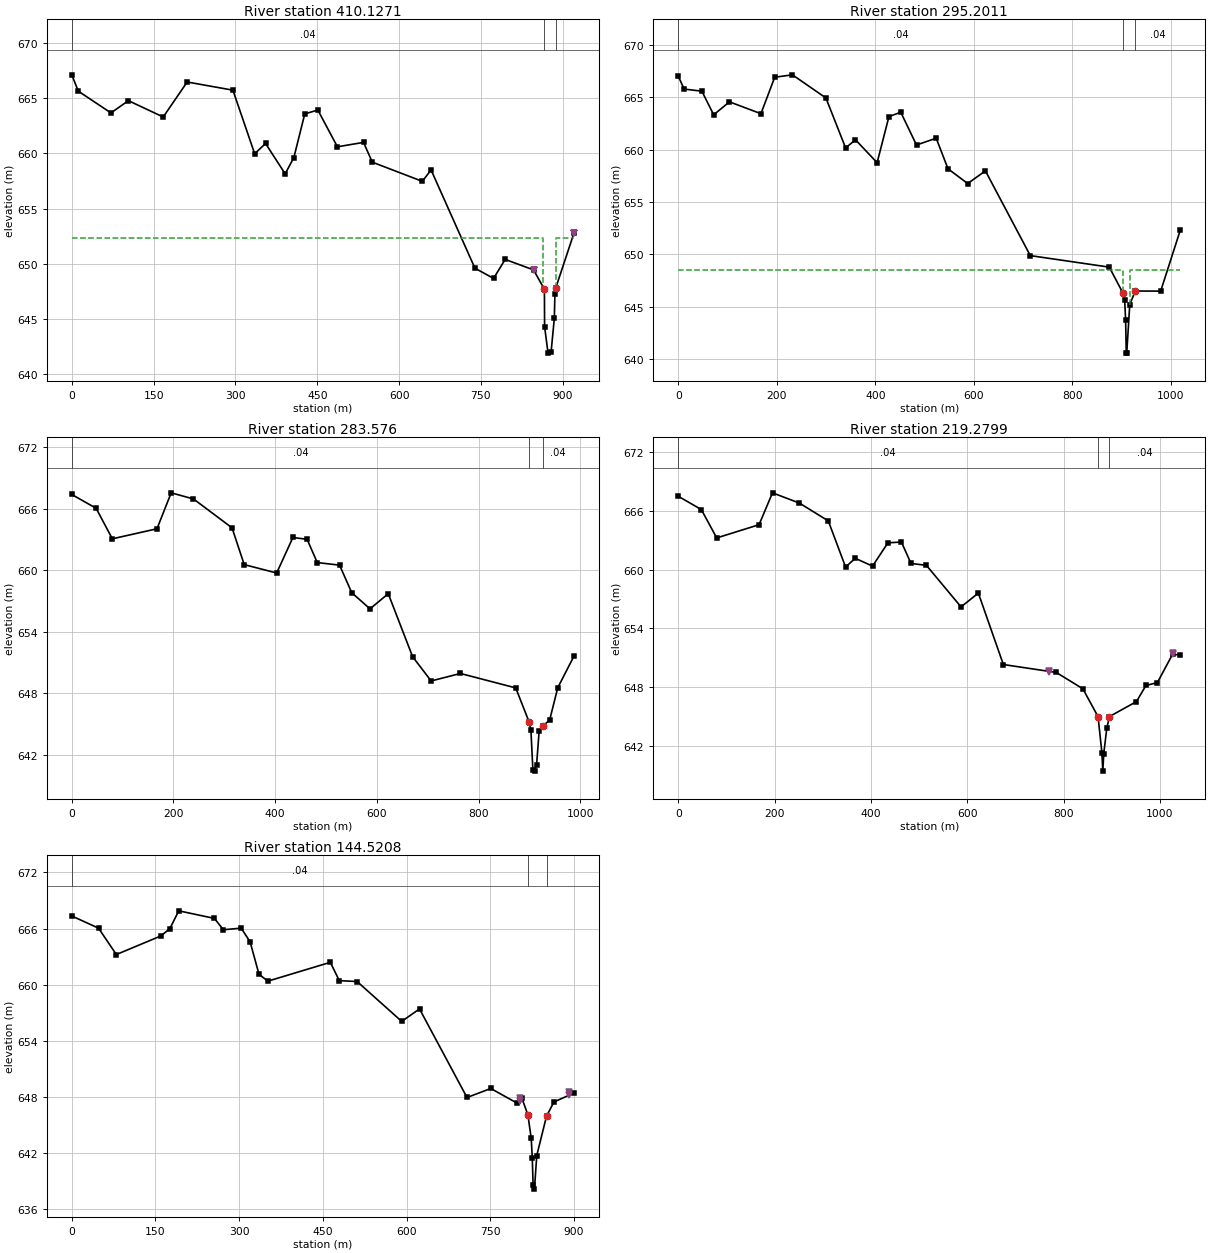
Type RM Length L Ch R = 1 ,410.1271,110.23,114.93,117.84
XS GIS Cut Line= 6
262504.9363319021515285.68417957262427.0100319021514593.58997957
262435.2800319021514477.94997957262439.1100319021514424.19997957
262436.0600319021514399.42997957262438.1293349971514370.46988557
#Sta/Elev= 30
       0  667.12   11.97  665.64   71.84  663.67  103.77  664.78  167.63   663.3
  211.53  666.47  295.35  665.73  335.26  659.97  355.22   660.9  391.14  658.15
   407.1  659.63  427.06  663.58  451.01  663.93  486.93   660.6  534.82     661
  550.79  659.21  642.59  657.47  658.55  658.51  739.01   649.6  773.18  648.68
  794.42   650.4  846.37  649.45  866.35   647.7  866.66  644.32  873.01  641.91
  878.51  641.98  884.52  645.06  885.58  647.27  886.82  647.77  920.29  652.75
#Mann= 3 , 0 , 0
       0     .04       0  866.35     .03       0  886.82     .04       0
Levee=-1,846.37,649.45,-1,920.29,652.75,Levee 4,Levee 5
#XS Ineff= 2 , 0
       0  864.34  652.37  886.82       0  652.37
Permanent Ineff=
       F       F
Bank Sta=866.35,886.82
XS Rating Curve= 0 ,0
Exp/Cntr=0.3,0.1

Type RM Length L Ch R = 1 ,295.2011,9.94,11.63,18.22
XS GIS Cut Line= 6
262514.0645319021515284.49357957262441.6815319011514584.91717957
262535.7100319011514494.98997957262550.6400319021514419.66997957
262552.7000319021514406.71997957262585.1671173471514316.81803746
#Sta/Elev= 30
       0  667.02   11.99  665.78   47.95  665.58   71.93  663.32   103.9  664.56
  167.84  663.43  195.81  666.91  231.77  667.14  299.71  664.93  339.67  660.16
  359.65  660.94   403.6  658.75  427.58  663.15  451.56  663.57  483.53  660.44
  523.49  661.09  547.46  658.17  587.43  656.76  623.39  657.97  714.47  649.88
  874.76  648.78  902.32  646.32  906.01  645.62  907.93  643.74   909.2  640.59
   910.2  640.57   916.3   645.2  927.51   646.5  979.08  646.49 1018.91  652.32
#Mann= 3 , 0 , 0
       0     .04       0  902.32     .03       0  927.51     .04       0
Levee=0,,,-1,1054.82,652.86,,Levee 5
#XS Ineff= 2 , 0
       0  902.32   648.5   916.3       0   648.5
Permanent Ineff=
       F       F
Bank Sta=902.32,927.51
XS Rating Curve= 0 ,0
Exp/Cntr=0.3,0.1

Type RM Length L Ch R = 1 ,283.576 ,53.24,64.3,66.17
XS GIS Cut Line= 6
262522.9192319021515284.59057957262451.3138319021514585.99097957
262536.9800319021514498.34997957262557.7300319021514423.15997957
262564.2600319021514413.84997957262613.2770958251514359.36205941
#Sta/Elev= 30
       0   667.4   47.88  666.05    79.8  663.07  167.58  664.05  195.52  667.56
  239.41  666.96  315.22  664.14  339.16  660.55     403  659.73  434.92   663.2
  462.85  663.02   482.8  660.75  526.69   660.5  550.64  657.81  586.55  656.23
  622.46  657.71  670.34  651.56  706.82  649.19  764.42  649.92  873.19  648.51
  899.34   645.2  903.03  644.38  906.93  640.49  910.83 640.385  914.25  641.03
   919.3  644.35  926.07  644.77  939.93  645.38  955.78  648.52  987.47  651.59
#Mann= 3 , 0 , 0
       0     .04       0  899.34     .03       0  926.07     .04       0
Levee=0,,,-1,1011.21,654.29,,Levee 5
Bank Sta=899.34,926.07
XS Rating Curve= 0 ,0
Exp/Cntr=0.3,0.1

Type RM Length L Ch R = 1 ,219.2799,73.35,74.76,75.23
XS GIS Cut Line= 6
262528.1562319021515284.16547957262457.1536319021514592.79377957
262510.3600319021514544.05997957262591.1600319021514473.14997957
262599.6700319011514468.90997957262711.2341818861514356.65460874
#Sta/Elev= 30
       0  667.49   47.93  666.13   79.89  663.23  167.76  664.58  195.72  667.84
  251.64  666.79  311.56  664.97   347.5  660.25  367.48  661.15  403.42  660.35
  435.38  662.73  463.34  662.81  483.31  660.62  515.26  660.43  587.16  656.18
  623.11  657.59  675.03  650.29  784.91  649.48  840.12  647.81  871.66  644.96
  879.68  641.26  881.57 639.394  883.45  641.16  889.75  643.76  895.27  644.97
  951.35   646.5  971.11  648.15  994.83  648.44 1026.47  651.35 1042.45  651.25
#Mann= 3 , 0 , 0
       0     .04       0  871.66     .03       0  895.27     .04       0
Levee=-1,769.62,649.55,-1,1027.42,651.43,Levee 6,Levee 5
Bank Sta=871.66,895.27
XS Rating Curve= 0 ,0
Exp/Cntr=0.3,0.1

Type RM Length L Ch R = 1 ,144.5208,69.91,70.27,70.72
XS GIS Cut Line= 6
262535.4512319021515283.19577957262468.4455319021514661.56567957
262549.5200319021514593.38997957262562.5300319021514584.27997957
262572.2700319021514577.43997957262687.6199810281514496.58001515
#Sta/Elev= 30
       0  667.34   47.94  666.0479.90002  663.22   159.8  665.21  175.78  665.99
  191.76  667.89  255.69  667.08  271.67  665.87  303.63  666.04  319.61  664.58
  335.59   661.1  351.57  660.38  463.43  662.39  479.41  660.43  511.37  660.34
  591.27  656.08  623.23  657.41  708.33  647.95  751.01  648.91  798.62  647.33
  806.57   647.9  817.48  646.09  823.38  643.61  825.33   641.5  826.76  638.65
   829.2  638.16  833.37  641.75  850.84  645.95   864.1  647.47  899.82  648.42
#Mann= 3 , 0 , 0
       0     .04       0  817.48     .03       0  850.84     .04       0
Levee=-1,802.6,647.9,-1,891.88,648.53,Levee 6,Levee 5
Bank Sta=817.48,850.84
XS Rating Curve= 0 ,0
Exp/Cntr=0.3,0.1