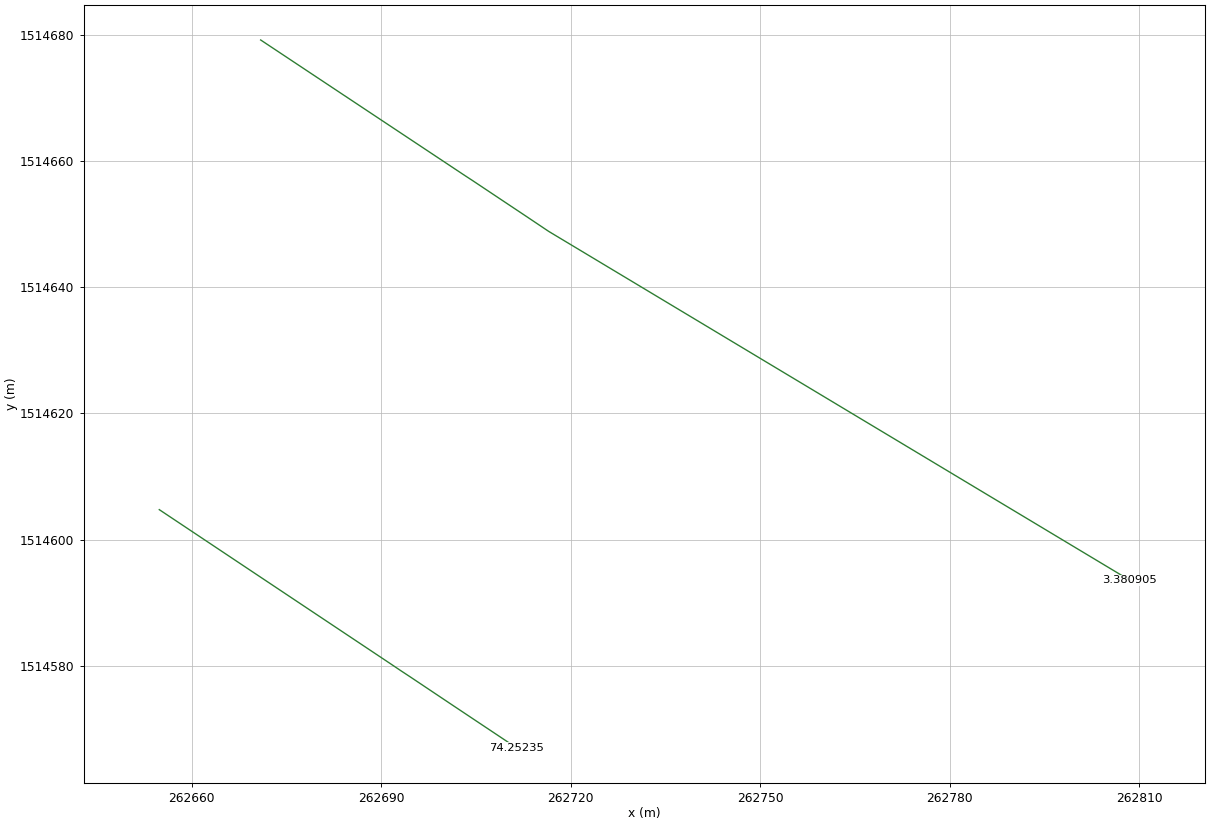
HEC-RAS study amss1_V6.prj: amss1_V6

--- amss1_V6.g01 (geometry) --- (continued)

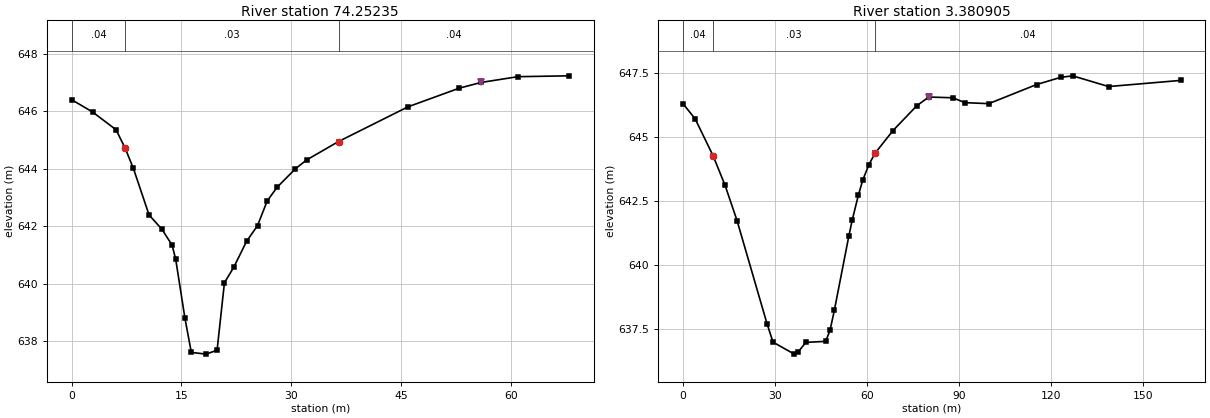
Type RM Length L Ch R = 1 ,74.25235,70.88,70.87,71.26
XS GIS Cut Line= 6
262654.8510511071514604.76929805262691.4300319021514580.38997957
262693.0800319021514579.27997957262694.7500319021514578.17997957
262701.3900319021514573.73997957262711.369168652 1514567.0905568
#Sta/Elev= 27
       0  646.412.869995  645.986.080017  645.367.320007  644.728.450012  644.01
 10.5899  642.3912.35004  641.8913.73004  641.3414.23004  640.8415.48004   638.8
16.36005   637.6 18.3999  637.54   19.88  637.68   20.88  640.0322.14001  640.56
 23.8999  641.47 25.3999  642.0226.71991  642.88 28.0899  643.3630.57001     644
   32.12  644.31 36.4599  644.9545.95001  646.1652.95001  646.81   55.94  647.01
   60.94  647.2167.93002  647.24
#Mann= 3 , 0 , 0
       0     .04       07.320007     .03       0 36.4599     .04       0
Levee=-1,-8.98999,647.51,-1,55.94,647.01,Levee 6,Levee 5
Bank Sta=7.320007,36.4599
XS Rating Curve= 0 ,0
Exp/Cntr=0.3,0.1

Type RM Length L Ch R = 1 ,3.380905,0,3.38,0
XS GIS Cut Line= 6
262670.9040459541514679.14730354262703.3900319021514657.57997957
262704.4200319011514656.90997957262713.1100319021514651.11997957
262716.5100319021514648.83997957262808.5419181961514593.58885678
#Sta/Elev= 30
       0   646.33.900009  645.72 9.76001  644.2713.67001  643.1117.57001  641.73
27.34001  637.6929.29001  636.97   36.23   636.537.53001  636.59   39.98  636.96
   46.44     637   47.87  637.43   49.27  638.2154.01001  641.1355.14001  641.77
57.14001  642.7458.58001  643.3360.54001  643.9262.49001  644.3668.35001  645.25
   76.16  646.2380.07004  646.5787.88004  646.5491.79001  646.3599.60001  646.31
  115.22  647.06  123.04  647.34  126.94   647.4  138.65  646.98   162.1  647.22
#Mann= 3 , 0 , 0
       0     .04       0 9.76001     .03       062.49001     .04       0
Levee=0,,,-1,80.07004,646.57,,Levee 5
Bank Sta=9.76001,62.49001
XS Rating Curve= 0 ,0
Exp/Cntr=0.3,0.1

Chan Stop Cuts=-1
Use User Specified Reach Order=0
Composite Channel Slope=5